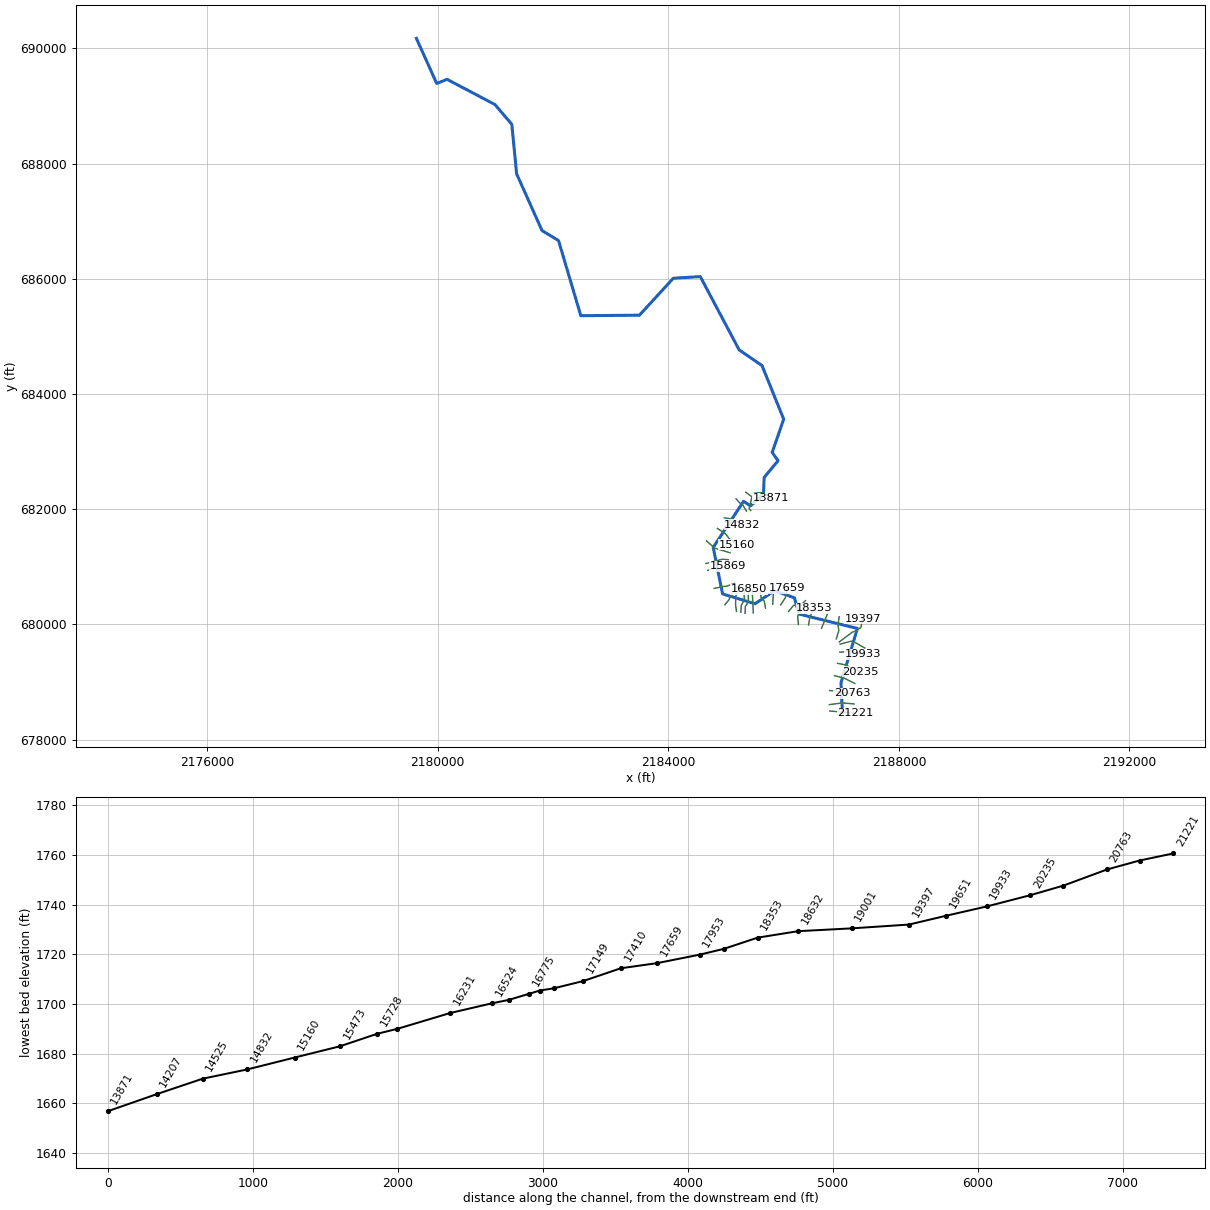
--- GRANDCMPRN.prj (project) ---

Proj Title=GRANDCMPRN
Current Plan=p01
Default Exp/Contr=0,0
English Units
Geom File=g01
Flow File=f01
Plan File=p01
BEGIN DESCRIPTION:
---------- MODELED AS PART OF WVEMD CTP PROGRAM, 2023----------
Stream Name: Grand Camp Run
Flood Zone:  AFH
Upshur County, WV
HEC-RAS Version: RAS 6.3
Vertical Datum: NAVD88
Projection: NAD 1983 StatePlane West Virginia S FIPS 4702 (US Feet)
Terrain: 1-meter LIDAR (FEMA Region III 3DEP collected 2016-2018)
Land Use: 2019 NLCD
Hydrologic Method:
WV SIR2010-5033 regression equations
Additional Model Notes:
Main stem is FRENCHCK
END DESCRIPTION:
DSS Export Rating Curves= 0
DSS Export Rating Curve Sorted= 0
DSS Export Volume Flow Curves= 0
DXF OffsetX= 0
DXF OffsetY= 0
DXF ScaleX= 0
DXF ScaleY= 0

--- GRANDCMPRN.p01 (plan) ---

Plan Title=Floodplain
Program Version=6.31
Short Identifier=Floodplain
Geom File=g01
Flow File=f01
Subcritical Flow
K Sum by GR= 0
Std Step Tol= 0.01
Critical Tol= 0.01
Num of Std Step Trials= 20
Max Error Tol= 0.3
Flow Tol Ratio= 0.001
Split Flow NTrial= 30
Split Flow Tol= 0.02
Split Flow Ratio= 0.02
Log Output Level= 0
Friction Slope Method= 1
Unsteady Friction Slope Method= 2
Unsteady Bridges Friction Slope Method= 1
Parabolic Critical Depth
Global Vel Dist= 0 , 0 , 0
Global Log Level= 0
CheckData=True
Encroach Param=-1 ,0,0, 0
Mapping Interval=1HOUR
Computation Time Step Use Courant=        0
Computation Time Step Use Time Series=    0
Computation Time Step Count To Double=0
Computation Time Step Max Doubling=0
Computation Time Step Max Halving=0
Computation Time Step Residence Courant=0
Run HTab= 0
Run UNet= 0
Run Sediment= 0
Run PostProcess= 0
Run WQNet= 0
Run RASMapper=-1
UNET Theta= 0
UNET Theta Warmup= 0
UNET ZTol= 0
UNET ZSATol= 0
UNET MxIter= 0
UNET Max Iter WO Improvement= 0
UNET MaxInSteps= 0
UNET DtIC= 0
UNET DtMin= 0
UNET MaxCRTS= 0
UNET WFStab= 0
UNET SFStab= 0
UNET WFX= 1
UNET SFX= 1
UNET Gravity=32.17405
UNET 1D Methodology=Finite Difference
UNET DSS MLevel= 1
UNET Pardiso=0
UNET DZMax Abort= 0
UNET Use Existing IB Tables= 0
UNET Froude Reduction=False
UNET Froude Limit= 0
UNET Froude Power= 0
UNET D1 Cores= 0
UNET WindReference=Eulerian
UNET WindDragFormulation=Hsu (1988)
UNET D2 Coriolis=0
UNET D2 Cores= 0
UNET D2 Theta= 1
UNET D2 Theta Warmup= 1
UNET D2 Z Tol= 0.01
UNET D2 Volume Tol= 0.01
UNET D2 Max Iterations= 20
UNET D2 Equation= 0
UNET D2 RampUpFraction=0.1
UNET D2 TimeSlices= 1
UNET D2 Turbulence Formulation=Non-Conservative (original)
UNET D2 Eddy Viscosity=0.3
UNET D2 Transverse Eddy Viscosity=0.1
UNET D2 Smagorinsky Mixing=0
UNET D2 BCVolumeCheck=0
UNET D2 Cores=0
UNET D2 SolverType=PARDISO (Direct)
UNET D2 Minimum Iterations= 3
UNET D2 Maximum Iterations= 30
UNET D2 Restart Number= 10
UNET D2 Relaxation Coeff=1.3
UNET D2 SOR Precondition Iterations= 10
UNET D2 ILUT Maximum Fill= 8
UNET D2 ILUT Tolerance=1E-08
UNET D2 Convergence Tolerance=0.00001
UNET D1D2 MaxIter= 0
UNET D1D2 ZTol=0.01
UNET D1D2 QTol=0.1
UNET D1D2 MinQTol=1
Write IC File= 0
Write IC File at Fixed DateTime=0
Write IC File at Sim End=0
Echo Input=False
Echo Parameters=False
Echo Output=False
Write Detailed= 0
HDF Write Warmup=0
HDF Write Time Slices=0
HDF Flush=0
HDF Compression= 1
HDF Chunk Size= 1
HDF Spatial Parts= 1
HDF Use Max Rows=0
HDF Fixed Rows= 1
Calibration Method= 0
Calibration Iterations= 20
Calibration Max Change=0.05
Calibration Tolerance=0.2
Calibration Maximum=1.5
Calibration Minimum=0.5
Calibration Optimization Method= 1
WQ AD Non Conservative
WQ ULTIMATE=-1
WQ Max Comp Step=1HOUR
WQ Output Interval=15MIN
WQ Output Selected Increments= 0
WQ Create Restart=0
WQ Fixed Restart=0
WQ System Summary=0
WQ Write To DSS=0
Sorting and Armoring Iterations= 10
XS Update Threshold= 0.02
Bed Roughness Predictor= 0
Hydraulics Update Threshold= 0.02
Energy Slope Method= 1
Volume Change Method= 1
Sediment Retention Method= 0
Sediment TS Multiplier= 1
Warm Up Method= 0
XS Weighting Method= 0
Number of US Weighted Cross Sections= 1
Number of DS Weighted Cross Sections= 1
Upstream XS Weight=0
Main XS Weight=1
Downstream XS Weight=0
Number of DS XS's Weighted with US Boundary= 1
Upstream Boundary Weight= 1
Weight of XSs Associated with US Boundary= 0
Number of US XS's Weighted with DS Boundary= 1
Downstream Boundary Weight= 0.5
Weight of XSs Associated with DS Boundary= 0.5
Percentile Method= 0
Sediment Output Level= 3
Mass or Volume Output= 0
Output Increment Type= 1
Profile and TS Output Increment= 1
Transport Output Increment 1
XS Output Flag= 0
XS Output Increment= 10
Read HDF5 Sediment Hotstart= 0
Sediment Hotstart Type= 0
Write Gradation File= 0
Read Gradation Hotstart= 0
Write HDF5 File= 1
Write Binary Output= 1
Write DSS Sediment File= 0
DSS Sediment Output Type= 1
SV Curve= 0
Specific Gage Flag= 0
Subcell Erosion Methods= 0
Subcell Deposition Methods= 0
Advection Scheme= 1
Matrix Solver= 0
Implicit Weighting Factor= 1
Maximum Outer Loop Convergence Iterations= 5
Convergence Maximum Absolute= 0.001
Convergence RMSE= 0.0001
Grain Fractions Max Abs Error= 0.001
Max Subgrid Regions= 1
Max Subgrid Length Scale= 3.402823E+38
Initial Layer Thickness= 3.402823E+38
Min Layer Thickness= 3.402823E+38
Max Layer Thickness= 3.402823E+38
Number of Layers= 5

--- GRANDCMPRN.f01 (steady flow) ---

Flow Title=Flows
Program Version=6.31
Number of Profiles= 1
Profile Names=01pct
River Rch & RM=GRANDCMPRN,Main,21221
     468
River Rch & RM=GRANDCMPRN,Main,16524
     543
River Rch & RM=GRANDCMPRN,Main,12531
     604
River Rch & RM=GRANDCMPRN,Main,10382
     685
River Rch & RM=GRANDCMPRN,Main,9002
     917
River Rch & RM=GRANDCMPRN,Main,7445
    1020
River Rch & RM=GRANDCMPRN,Main,4098
    1170
Boundary for River Rch & Prof#=GRANDCMPRN,Main            , 1
Up Type= 0
Dn Type= 3
Dn Slope=0.00147
DSS Import GetInterval= 0
DSS Import GetPeak= 0
DSS Import FillOption= 0

--- GRANDCMPRN.g01 (geometry) ---

Geom Title=Geometry
Program Version=6.31

River Reach=GRANDCMPRN      ,Main
Reach XY= 30
2187020.09227778678470.617534723     2186995.104       678985.15
     2187280.982      679928.833     2186269.278      680178.224
     2186186.405      680461.5552185842.26513412680584.342573177
2185504.29732785680357.470549749     2184940.676      680528.575
     2184778.937      681336.158     2185304.906      682135.929
     2185425.152       682057.72     2185650.907      682256.175
     2185662.525      682550.8662185903.73637131682841.327631457
     2185801.715      682984.3192186001.26601436683561.635561124
     2185625.467      684492.488     2185228.672      684764.229
     2184554.613      686036.857     2184086.191      686008.212
     2183499.212      685367.062     2182481.727      685357.819
     2182095.234      686662.269     2181808.842       686835.77
     2181367.863       687820.66     2181284.647      688679.924
     2180990.899      689023.9792180160.86369248689461.657085955
     2179981.628      689389.124     2179628.702      690172.956

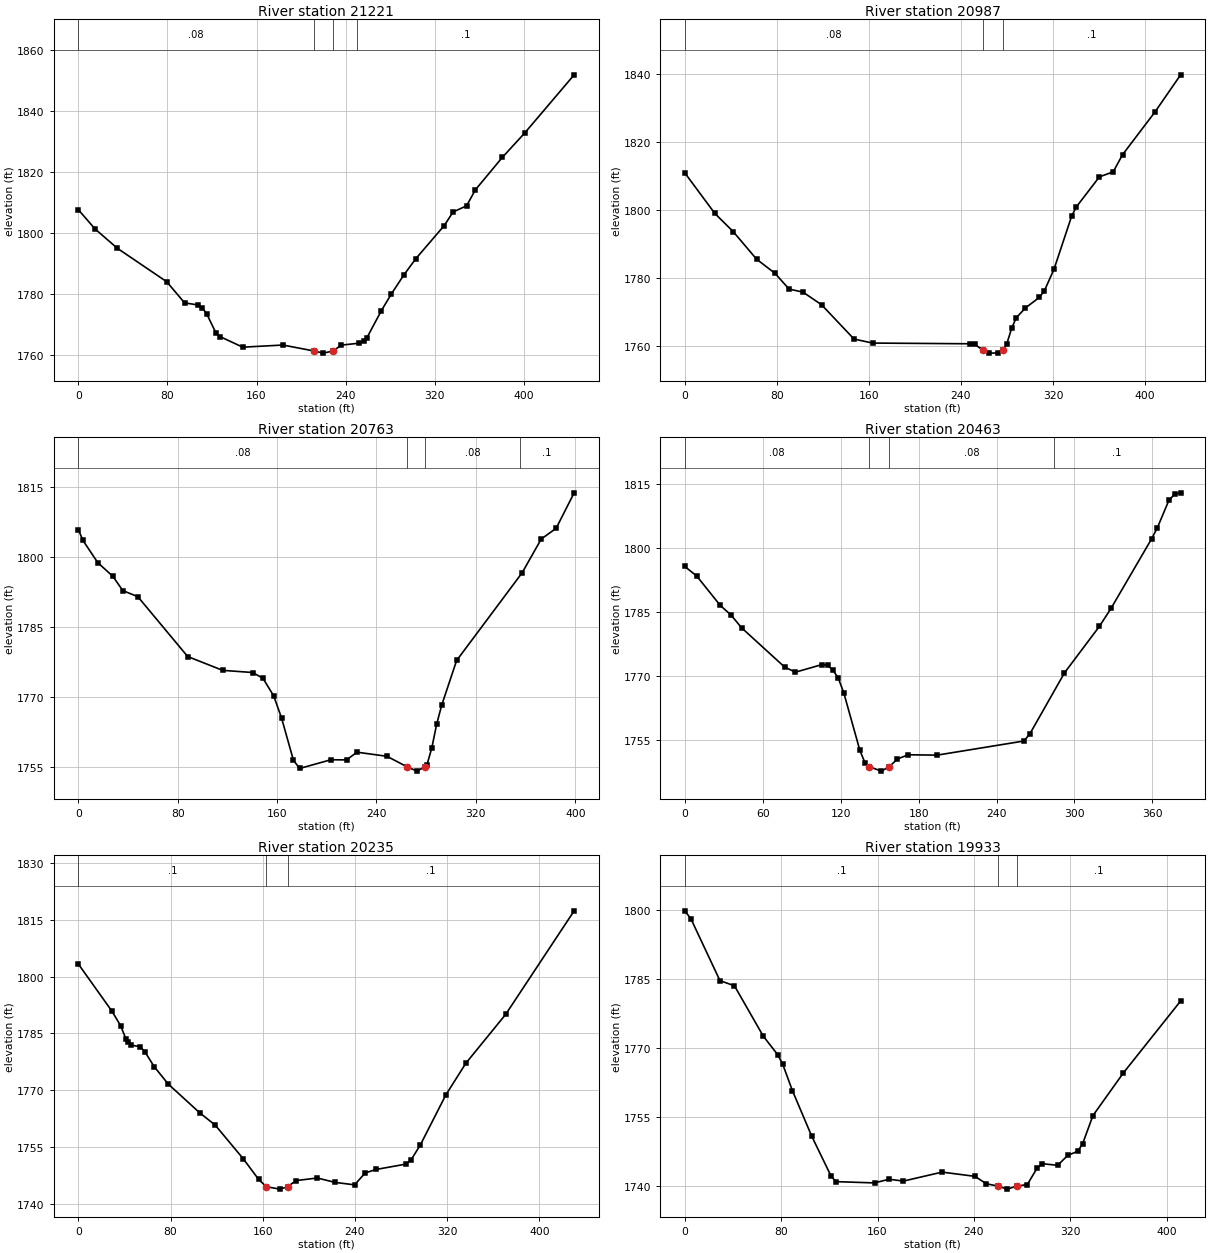
Type RM Length L Ch R = 1 ,21221   ,229.2,233.8,229.9
XS GIS Cut Line= 2
2186801.23437987678496.3062229562187244.41303485678454.722680543
#Sta/Elev= 30
       0 1807.63      15 1801.32    35.1 1794.97    79.3 1784.05    95.4 1777.11
   107.4 1776.43   111.4 1775.47   115.4 1773.39   123.5 1767.29   127.5 1766.01
   147.6  1762.6   183.7  1763.3   211.3 1761.37   219.9 1760.65   228.8 1761.37
     236 1763.27     252  1763.9   256.1 1764.51     259 1765.65   272.1 1774.61
     281 1780.02   292.2 1786.25   303.1 1791.64   328.4  1802.4   336.4 1806.88
   348.5 1808.89   356.5 1814.17   380.6 1824.75   400.7 1832.74   445.1  1851.8
#Mann= 4 ,-1,0
       0     .08       0   211.3    .045       0   228.8     .08       0
     250      .1       0
Bank Sta=211.3,228.8
XS Rating Curve= 0 ,0
Exp/Cntr=0.3,0.1

Type RM Length L Ch R = 1 ,20987   ,221.4,224,221.6
XS GIS Cut Line= 3
2186794.30291973 678606.714602632187023.91056249678636.715531223
2187222.52158888678618.157880146
#Sta/Elev= 30
       0 1810.78    26.1 1798.86    42.2 1793.46    62.4  1785.4    78.5 1781.22
    90.6 1776.62   102.7 1775.72   118.9    1772   147.1 1761.92   163.2 1760.74
   247.9 1760.53   251.9 1760.41     259 1758.68     264 1757.78     272 1757.82
  276.92 1758.67     280 1760.61   284.1 1765.07   288.1 1768.17   296.1 1771.07
   308.2 1774.16   312.6 1776.13     321 1782.52   336.3 1798.08   340.3 1800.75
   360.4 1809.61   372.4 1811.09   380.5 1816.12   408.6 1828.64     431 1839.61
#Mann= 3 ,-1,0
       0     .08       0     259    .045       0  276.92      .1       0
Bank Sta=259,276.92
XS Rating Curve= 0 ,0
Exp/Cntr=0.3,0.1

Type RM Length L Ch R = 1 ,20763   ,302.5,300.7,297.3
XS GIS Cut Line= 4
2186796.52771437678851.6749776912186937.71181196678838.148880243
2187017.27137944678812.3456160742187190.63155792678802.157924111
#Sta/Elev= 30
       0 1805.83     3.7 1803.51    15.7 1798.74    27.8 1795.83    35.8 1792.78
    47.9 1791.48      88 1778.69   116.2 1775.73   140.3 1775.27   148.6 1774.04
   157.3 1770.25   163.6 1765.52   173.1 1756.55   178.1 1754.76   203.3 1756.62
   215.9 1756.59   224.3 1758.24   248.4 1757.36  264.29 1755.16   272.5 1754.19
   279.4 1755.17   280.5 1755.43   284.5 1759.14   288.5  1764.3   292.5  1768.3
   304.5 1777.84   357.2 1796.58   372.6  1803.8   384.6  1806.1   399.1 1813.68
#Mann= 4 ,-1,0
       0     .08       0  264.29    .045       0   279.4     .08       0
  355.47      .1       0
Bank Sta=264.29,279.4
XS Rating Curve= 0 ,0
Exp/Cntr=0.3,0.1

Type RM Length L Ch R = 1 ,20463   ,231.3,228,223.9
XS GIS Cut Line= 3
2186881.74966975679109.9983749642187050.21236162679066.160794642
2187236.25761598678973.929352655
#Sta/Elev= 30
       0 1795.58     9.2 1793.34    27.3 1786.47    35.6 1784.22    43.8 1781.21
    76.9 1772.03    85.2 1770.85   105.8 1772.64     110 1772.43     114 1771.36
   118.2 1769.43   122.4    1766   134.8 1752.52   138.9  1749.5   141.9 1748.74
   151.3 1747.69  157.29  1748.7   163.7 1750.53     172 1751.52   194.2 1751.43
   261.1 1754.74   265.6 1756.39   292.3 1770.69   319.1 1781.54   328.1 1785.76
   359.3 1802.02   363.8 1804.65   372.7 1811.09   377.2 1812.52   381.7 1812.82
#Mann= 4 ,-1,0
       0     .08       0   141.9    .045       0  157.29     .08       0
  284.07      .1       0
Bank Sta=141.9,157.29
XS Rating Curve= 0 ,0
Exp/Cntr=0.3,0.1

Type RM Length L Ch R = 1 ,20235   ,296.3,302.1,301.7
XS GIS Cut Line= 4
2186935.48882601679323.374566975 2187081.0988031 679295.80872866
2187176.73419201 679240.110080372187335.10975441679174.677883975
#Sta/Elev= 30
       0 1803.34    29.2 1790.85    36.7 1787.02    41.4 1783.46    43.5 1782.63
    45.5 1781.91    53.6 1781.48    57.7 1780.16    65.8 1776.22      78 1771.61
   105.2 1764.04   118.8 1760.75   143.2 1751.82   156.4 1746.43   163.1 1744.48
   174.9 1743.84   181.6 1744.48   188.8 1746.09   207.3 1746.78   222.6 1745.63
   239.7 1744.97   248.9 1748.12   258.2 1749.03   284.2 1750.45   288.6 1751.52
   296.7  1755.5   318.9 1768.75   336.2  1777.1   370.8 1790.03   430.2 1817.39
#Mann= 3 ,-1,0
       0      .1       0   163.1    .045       0   181.6      .1       0
Bank Sta=163.1,181.6
XS Rating Curve= 0 ,0
Exp/Cntr=0.3,0.1

Type RM Length L Ch R = 1 ,19933   ,286.3,281.2,275.9
XS GIS Cut Line= 3
2186975.06523673679516.8549866532187199.46105806679532.370227764
2187377.64152674679476.847093911
#Sta/Elev= 30
       0 1799.77     5.1 1798.03    29.2 1784.59    41.2 1783.48    65.1 1772.55
    77.3 1768.44    81.3 1766.42    89.3 1760.71   105.4 1750.76   121.4 1742.13
   125.4 1740.91   157.5 1740.63   169.5 1741.43   181.5 1741.03   213.6 1742.98
   240.8 1742.06   250.4 1740.44  259.76 1739.96   267.6 1739.28   275.81739.958
   284.3 1740.27   292.7 1743.94   296.9 1744.81   309.5 1744.45   317.9 1746.61
   326.2 1747.51   330.3 1749.18   338.8 1755.26   363.9 1764.48   411.6 1780.17
#Mann= 3 ,-1,0
       0      .1       0  259.76    .045       0   275.8      .1       0
Bank Sta=259.76,275.8
XS Rating Curve= 0 ,0
Exp/Cntr=0.3,0.1

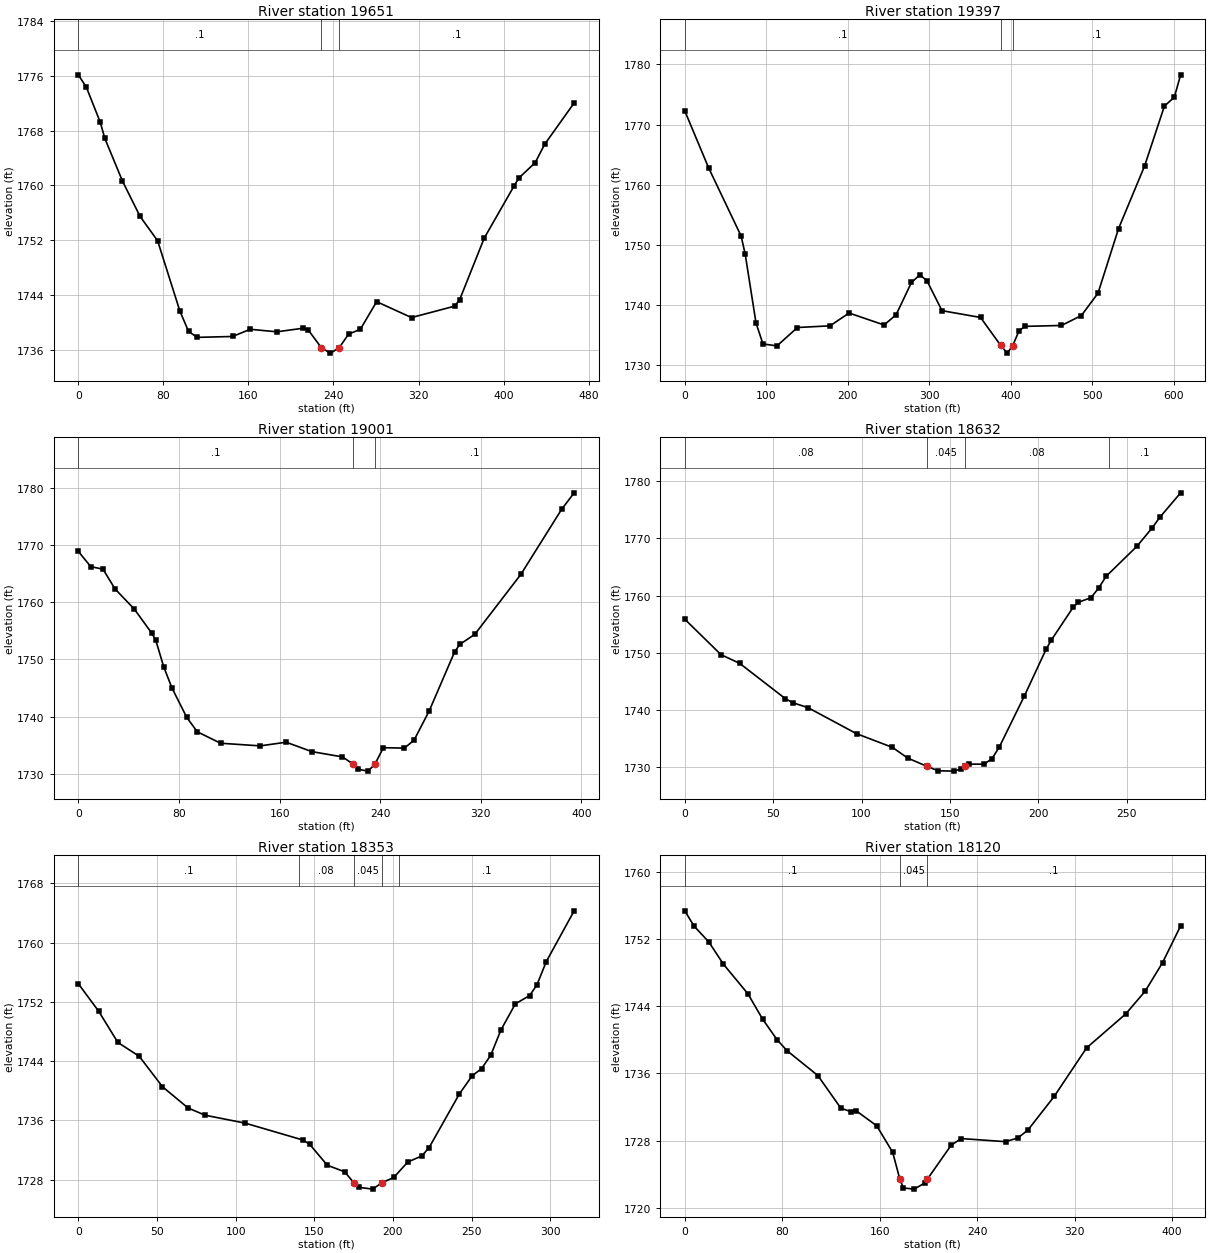
Type RM Length L Ch R = 1 ,19651   ,241,254.3,262.7
XS GIS Cut Line= 4
2186980.17651797679655.9041206042187174.96641072679709.066776814
2187245.10995049679683.7392868662187409.27089722679588.228379445
#Sta/Elev= 30
       0 1776.14     7.6 1774.31    20.7 1769.19    24.9 1766.87    41.5 1760.64
      58  1755.5    74.6 1751.92    95.5 1741.68   103.7 1738.69   111.9 1737.83
   145.1 1737.96   161.7 1739.01   186.7 1738.64   211.7 1739.17     216 1738.97
   228.7  1736.3   237.1 1735.53  245.25 1736.29   254.2  1738.3   265.3 1739.01
   280.6 1743.04   313.4 1740.72   354.1 1742.39   358.7 1743.33   381.8 1752.31
   409.6 1759.85   414.2 1761.05   429.8 1763.34   438.6 1765.99   466.4 1772.04
#Mann= 3 ,-1,0
       0      .1       0   228.7    .045       0  245.25      .1       0
Bank Sta=228.7,245.25
XS Rating Curve= 0 ,0
Exp/Cntr=0.3,0.1

Type RM Length L Ch R = 1 ,19397   ,380.9,395.8,409.6
XS GIS Cut Line= 5
2186964.90359284679694.1388063342187191.23520454 679864.21218892
2187249.47279335679886.5087452522187340.35417206679944.335292764
2187369.91686595680096.696830492
#Sta/Elev= 30
       0 1772.28    29.1 1762.85    69.1 1751.47    74.1 1748.47    87.4    1737
    95.9 1733.53   113.1  1733.2   138.2 1736.26   178.2 1736.54   201.6 1738.67
   244.5 1736.68   259.3 1738.38   278.1 1743.75   288.4 1745.01     297 1744.07
   315.6 1739.06   362.9 1737.93   387.7 1733.27   395.7    1732  402.32 1733.25
   410.2 1735.73   417.5 1736.45   462.2  1736.6   486.6 1738.25     507 1741.96
   532.2  1752.7   564.1 1763.09   588.5 1773.08   600.7 1774.56   608.4 1778.28
#Mann= 3 ,-1,0
       0      .1       0   387.7    .045       0  402.32      .1       0
Bank Sta=387.7,402.32
XS Rating Curve= 0 ,0
Exp/Cntr=0.3,0.1

Type RM Length L Ch R = 1 ,19001   ,373.1,369.6,357.4
XS GIS Cut Line= 4
2186914.72282728679746.388582959 2186958.8844804679897.725740055
2186942.16719664679987.5761054912186964.53251165680130.969842038
#Sta/Elev= 30
       0 1768.84     9.9 1766.18    19.6 1765.74    29.2 1762.28    44.6 1758.74
    58.3 1754.58    61.5 1753.37    67.9 1748.68    74.4 1745.01    86.2 1739.85
    94.6 1737.34   113.1 1735.34   144.6 1734.88   165.2 1735.52   185.6 1733.88
     210 1732.95   218.6 1731.68   222.2 1730.82   230.3 1730.47  235.78 1731.68
   242.5 1734.56   259.2 1734.49   266.9 1735.87     279 1741.01   299.2 1751.32
   303.3  1752.6   315.2 1754.36   351.9 1764.85   384.3 1776.21   394.2 1779.07
#Mann= 3 ,-1,0
       0      .1       0   218.6    .045       0  235.78      .1       0
Bank Sta=218.6,235.78
XS Rating Curve= 0 ,0
Exp/Cntr=0.3,0.1

Type RM Length L Ch R = 1 ,18632   ,276.8,278.6,274.9
XS GIS Cut Line= 2
2186658.05051165679932.510338349 2186764.6417321 680192.09517272
#Sta/Elev= 30
       0 1755.87    20.5 1749.67      31 1748.17    56.9 1741.99    61.3 1741.26
    69.6 1740.44    97.2 1735.87   117.5 1733.48   126.1 1731.62     137 1730.17
   143.4 1729.39   152.1 1729.33   156.4 1729.71   158.7 1730.18   160.7 1730.55
   169.4 1730.55   173.8 1731.49     178 1733.54   192.2 1742.48   204.5 1750.64
   207.5 1752.26   219.8 1757.96   222.8 1758.84   229.9 1759.63   234.2 1761.32
   238.5 1763.38   255.8 1768.59   264.5 1771.82   268.8 1773.66   280.6 1777.95
#Mann= 4 ,-1,0
       0     .08       0     137    .045       0   158.7     .08       0
     240      .1       0
Bank Sta=137,158.7
XS Rating Curve= 0 ,0
Exp/Cntr=0.3,0.1

Type RM Length L Ch R = 1 ,18353   ,229.5,233,229.3
XS GIS Cut Line= 4
2186432.62765183 679988.353718852186455.65905486680130.475697292
2186488.30534056680196.5957855792186535.42698944680281.956336438
#Sta/Elev= 30
       0 1754.45      13 1750.72    25.1 1746.53    38.7 1744.66    53.5 1740.55
    69.7 1737.69    80.5 1736.71   106.2 1735.63   142.7 1733.36     147 1732.79
   158.3 1729.95   169.3 1729.07   175.2 1727.58   178.2 1726.98   187.1 1726.73
   192.9 1727.58   200.5  1728.3   209.4 1730.38   218.4 1731.22     223 1732.34
   242.3  1739.6   250.4 1742.04   256.3 1742.98   262.2 1744.81   268.6 1748.19
   277.8 1751.73   286.9 1752.86   291.5 1754.28   297.5 1757.45   315.2 1764.29
#Mann= 5 ,-1,0
       0      .1       0     140     .08       0   175.2    .045       0
   192.9     .08       0  203.98      .1       0
Bank Sta=175.2,192.9
XS Rating Curve= 0 ,0
Exp/Cntr=0.3,0.1

Type RM Length L Ch R = 1 ,18120   ,184.3,167,149.2
XS GIS Cut Line= 4
2186255.83554165679997.5904901762186244.37971249680137.991012484
2186277.78091167 680213.403026792186399.25953661680350.977338205
#Sta/Elev= 30
       0 1755.35     7.6 1753.53    19.7 1751.65    31.7    1749    51.8 1745.47
    63.8 1742.47    75.8 1739.99    83.9  1738.7   109.2 1735.74     128 1731.87
     136 1731.45   140.9 1731.52   157.5 1729.76   170.6  1726.6   176.5 1723.39
   179.4 1722.36   188.1 1722.22   196.9 1722.94  198.94 1723.38   218.7 1727.47
     227 1728.24   263.2 1727.87   273.1  1728.3   281.4 1729.22   303.1 1733.25
   329.7 1739.03   361.8 1743.07   377.8 1745.78   392.1 1749.19   406.9 1753.56
#Mann= 3 ,-1,0
       0      .1       0   176.5    .045       0  198.94      .1       0
Bank Sta=176.5,198.94
XS Rating Curve= 0 ,0
Exp/Cntr=0.3,0.1

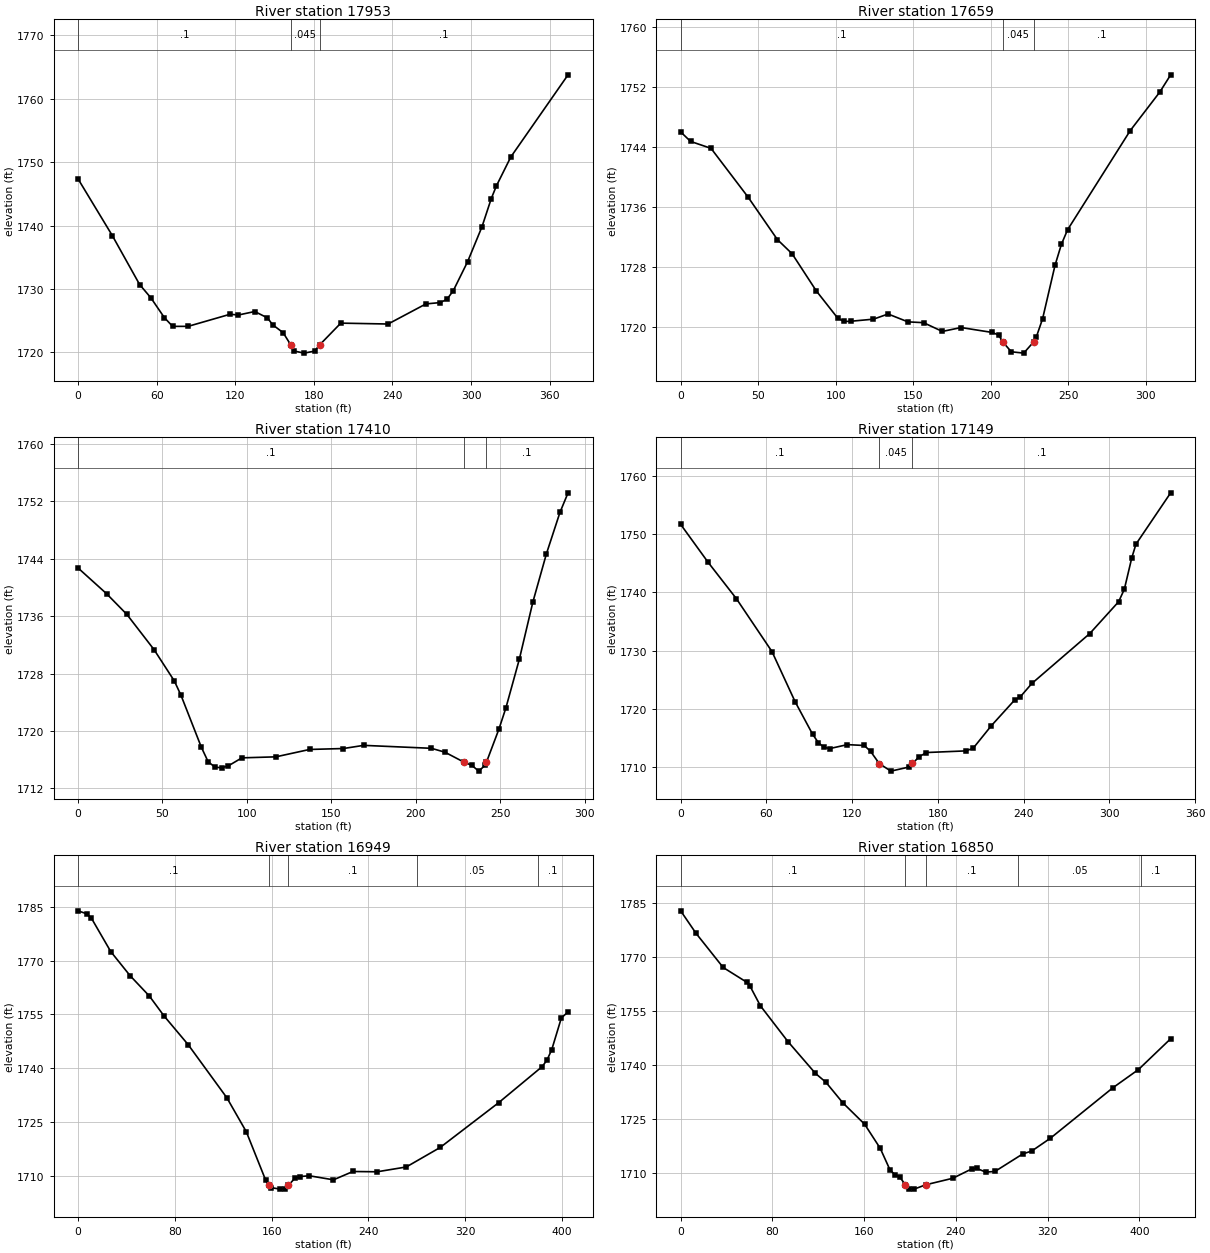
Type RM Length L Ch R = 1 ,17953   ,273.9,294.3,316.7
XS GIS Cut Line= 4
2186086.11580662680224.9705437572186175.06779364 680332.39589284
2186301.12342284680337.6852238822186379.95029258680412.196941387
#Sta/Elev= 30
       0 1747.35    26.2  1738.4      47  1730.7    55.6  1728.6    65.9 1725.48
    72.2  1724.1      84  1724.1   116.1 1726.01   122.4 1725.89   134.9 1726.44
   144.6 1725.44   148.6 1724.35   156.6  1723.1  162.36 1721.19   164.6 1720.23
   172.6 1719.88   180.6  1720.2   184.6 1721.21   200.6 1724.61   236.7 1724.47
   265.6 1727.64   276.5 1727.85   281.6 1728.36   286.4 1729.69   297.4 1734.29
   308.4 1739.81   315.5 1744.26   319.4 1746.25   330.4 1750.81   374.1 1763.76
#Mann= 3 ,-1,0
       0      .1       0  162.36    .045       0   184.6      .1       0
Bank Sta=162.36,184.6
XS Rating Curve= 0 ,0
Exp/Cntr=0.3,0.1

Type RM Length L Ch R = 1 ,17659   ,246.3,249.1,247.8
XS GIS Cut Line= 3
 2185948.7244931 680336.748082482186030.85298117680464.092587271
2186054.35697321680626.924322293
#Sta/Elev= 30
       0 1746.03     6.4 1744.76    19.6 1743.83    43.4 1737.34    62.4 1731.64
    71.9 1729.74    87.5 1724.78   101.2 1721.17   105.2 1720.69   109.7 1720.72
   124.4    1721   133.8 1721.69   146.6 1720.64   156.7 1720.53   168.8 1719.36
   180.9 1719.88   201.1 1719.22   205.2 1718.86   207.71717.982   213.3 1716.64
   221.3 1716.46  227.66 1717.95   229.4 1718.59   233.5 1721.07   241.5  1728.2
   245.6    1731   249.6 1732.95     290  1746.2   309.1 1751.36   316.1 1753.66
#Mann= 3 ,-1,0
       0      .1       0   207.7    .045       0  227.66      .1       0
Bank Sta=207.7,227.66
XS Rating Curve= 0 ,0
Exp/Cntr=0.3,0.1

Type RM Length L Ch R = 1 ,17410   ,247.2,260.2,264.2
XS GIS Cut Line= 2
2185811.27873988680348.2824578972185826.67694979680637.951927272
#Sta/Elev= 30
       0 1742.72    16.9 1739.13    28.9 1736.25      45 1731.34      57 1726.98
      61 1724.95      73 1717.74      77 1715.73      81 1714.97      85 1714.87
      89 1715.15      97 1716.26   117.1  1716.4   137.1 1717.43   157.1 1717.56
   169.1    1718   209.2 1717.59   217.2 1717.05   228.4 1715.67   233.2 1715.21
   237.2 1714.41   241.2 1715.27  241.78 1715.65   249.2 1720.28   253.3 1723.22
   261.3 1730.04   269.3    1738   277.3  1744.7   285.3 1750.46   290.1 1753.19
#Mann= 3 ,-1,0
       0      .1       0   228.4    .045       0  241.78      .1       0
Bank Sta=228.4,241.78
XS Rating Curve= 0 ,0
Exp/Cntr=0.3,0.1

Type RM Length L Ch R = 1 ,17149   ,208.7,200.5,188.3
XS GIS Cut Line= 4
2185686.34047621680282.2437726692185665.81833483680400.148200877
2185608.90029805680467.8938153882185589.41758018680601.212613629
#Sta/Elev= 30
       0  1751.7    19.2 1745.18      39 1738.92    63.9 1729.82    80.1 1721.19
    92.3 1715.61    96.4 1714.14   100.4 1713.32   104.5 1713.14   116.7 1713.81
   128.5 1713.66   132.9 1712.65  138.99 1710.55   147.1 1709.25   159.5 1709.94
   162.21710.566     167 1711.74     172 1712.45   199.4 1712.73   204.6 1713.16
   217.5 1717.09   233.7 1721.48   237.8 1722.07   245.8 1724.34   286.3 1732.92
   306.5  1738.4   310.5 1740.56   315.7 1745.96   318.6 1748.29   342.9 1757.13
#Mann= 3 ,-1,0
       0      .1       0  138.99    .045       0   162.2      .1       0
Bank Sta=138.99,162.2
XS Rating Curve= 0 ,0
Exp/Cntr=0.3,0.1

Type RM Length L Ch R = 1 ,16949   ,102.7,99.3,92.8
XS GIS Cut Line= 3
2185473.24914775680198.2220129882185466.21516366680387.950377983
2185452.31524403680602.638898686
#Sta/Elev= 30
       0 1783.86       7 1783.06      11 1781.84      27 1772.53      43 1765.81
      59 1760.11      71 1754.62      91  1746.6     123  1731.8   139.1 1722.32
   155.1 1708.83  157.92 1707.38   159.1  1706.8   167.1 1706.36   171.1 1706.49
   173.81707.382   179.1 1709.35   183.1 1709.85   191.1 1710.08   211.1 1708.95
   227.2 1711.27   247.2 1711.19   271.3 1712.53   299.3 1717.96   347.6 1730.42
   383.5 1740.45   387.5 1742.24   391.5 1745.17   399.5 1754.07     405 1755.68
#Mann= 5 ,-1,0
       0      .1       0  157.92    .045       0   173.8      .1       0
  279.86     .05       0  379.86      .1       0
Bank Sta=157.92,173.8
XS Rating Curve= 0 ,0
Exp/Cntr=0.3,0.1

Type RM Length L Ch R = 1 ,16850   ,74.5,74.8,74.9
XS GIS Cut Line= 6
2185330.93034031680191.7451578172185336.02967522680311.611827721
2185363.25549602680352.6245952272185389.49970997  680430.5553744
2185386.22603437680490.5727603392185399.86054165680605.426123885
#Sta/Elev= 30
       0 1782.77    13.4 1776.52    37.1 1767.02    57.5 1762.95    60.2 1762.01
    69.5 1756.39    93.5 1746.45   117.5  1737.6   126.7 1735.11   141.3 1729.45
   160.4 1723.47     174 1716.78   182.5  1710.8   186.7 1709.45   190.9 1708.83
     196 1706.63   199.3 1705.52   203.6 1705.42  213.77 1706.63   237.3 1708.44
   254.1 1711.08   258.1  1711.2   266.1 1710.14   274.1 1710.34   298.2 1715.18
   306.2 1716.02   322.3 1719.54   376.9 1733.59   399.2 1738.65   427.3 1747.22
#Mann= 5 ,-1,0
       0      .1       0     196    .045       0  213.77      .1       0
  294.35     .05       0   401.6      .1       0
Bank Sta=196,213.77
XS Rating Curve= 0 ,0
Exp/Cntr=0.3,0.1

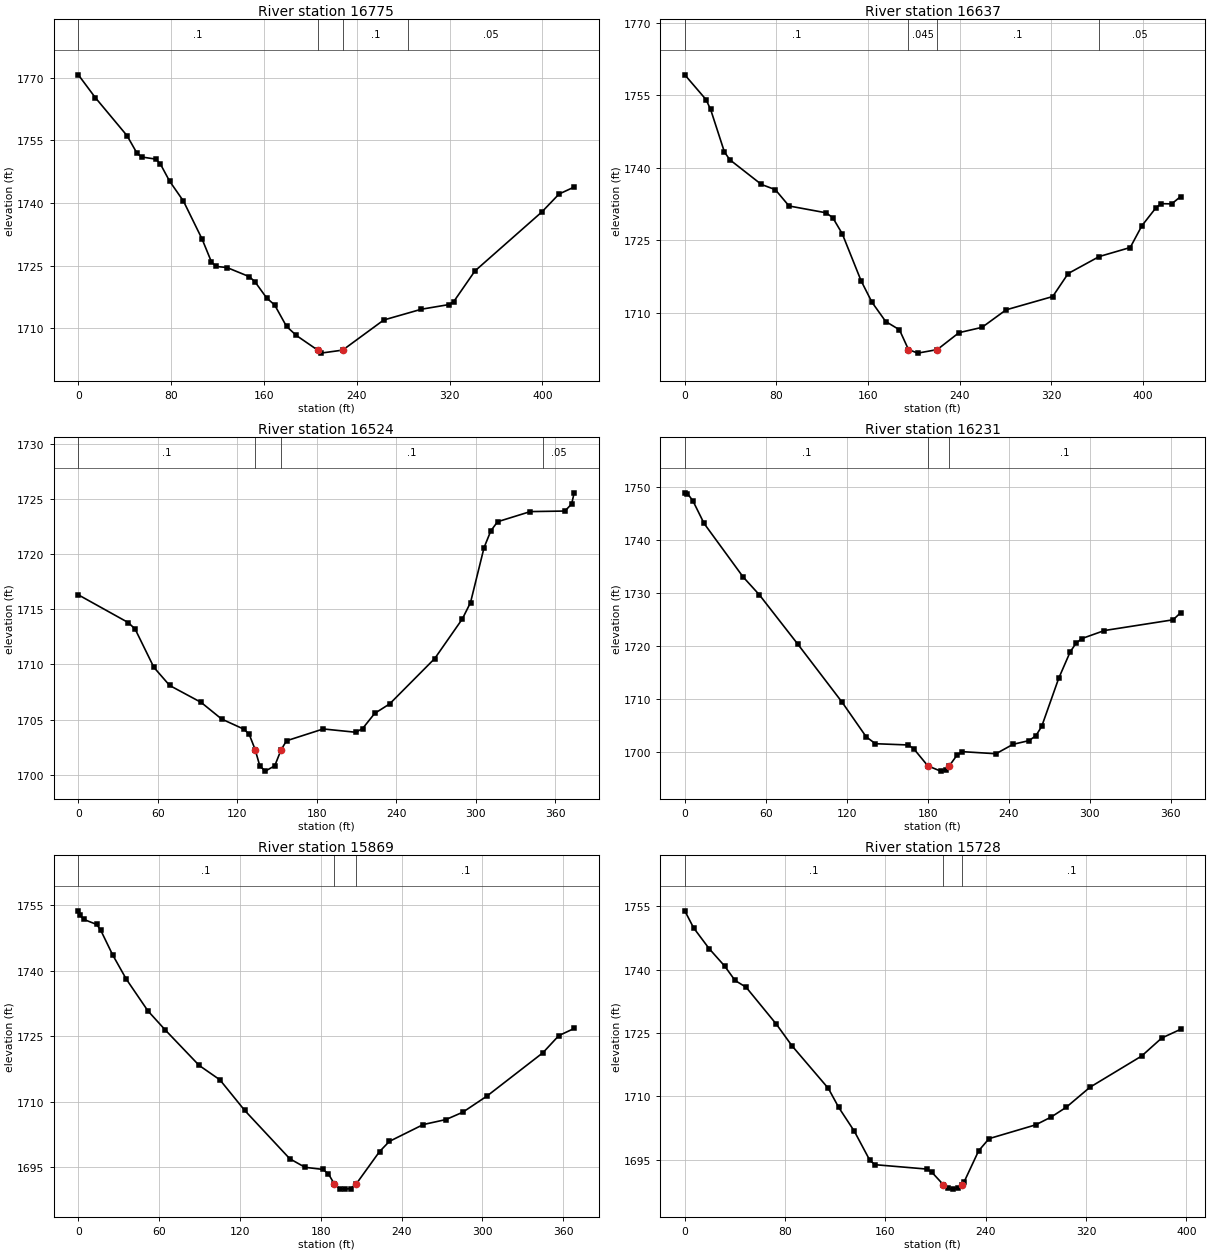
Type RM Length L Ch R = 1 ,16775   ,133.8,138.2,142.8
XS GIS Cut Line= 6
 2185259.0067918 680210.62018898 2185264.1061267680330.486858884
 2185291.3319475680371.4996263892185317.57616145680449.430405563
2185314.30248585680509.4477915022185327.93699313680624.301155048
#Sta/Elev= 30
       0 1770.65    14.6 1765.21      42 1756.09    50.6 1751.88    54.6    1751
    66.6  1750.5    70.6 1749.38    78.6 1745.25    90.6 1740.45   106.7 1731.34
   114.7 1725.92   118.7 1724.83   128.1 1724.57   147.4 1722.38   152.2 1721.17
   162.3 1717.29   169.2 1715.61   179.4  1710.5   187.9 1708.32  206.12 1704.85
     209  1704.1   227.8 1704.82   263.2 1712.02   295.7  1714.6   319.4 1715.71
   323.4 1716.37   341.8 1723.75   399.5 1737.87   414.3 1742.15   427.3 1743.81
#Mann= 4 ,-1,0
       0      .1       0  206.12    .045       0   227.8      .1       0
  284.35     .05       0
Bank Sta=206.12,227.8
XS Rating Curve= 0 ,0
Exp/Cntr=0.3,0.1

Type RM Length L Ch R = 1 ,16637   ,113.6,112.8,110.4
XS GIS Cut Line= 4
2185181.59155942680222.7967344112185165.79854419680353.078385279
2185171.75782229680492.9349625322185246.85580638680636.106051672
#Sta/Elev= 30
       0 1759.22    18.5 1754.11    22.5 1752.09    34.6 1743.26    39.3 1741.66
    66.9 1736.55      79 1735.48      91  1732.1   123.3 1730.69   129.2 1729.68
   137.5 1726.34   153.9 1716.64   163.4  1712.2   175.4 1708.21   187.4  1706.5
   195.3  1702.4   203.4 1701.67  220.42  1702.4   239.4  1705.9   259.5    1707
   280.5 1710.62   321.2 1713.37   334.7 1718.13   361.8 1721.64   388.9 1723.51
   399.1 1728.02   411.5 1731.77     416 1732.58   425.1 1732.53   432.9 1734.05
#Mann= 4 ,-1,0
       0      .1       0   195.3    .045       0  220.42      .1       0
  361.22     .05       0
Bank Sta=195.3,220.42
XS Rating Curve= 0 ,0
Exp/Cntr=0.3,0.1

Type RM Length L Ch R = 1 ,16524   ,307.6,292.4,265.5
XS GIS Cut Line= 4
2184980.75068976 680340.352998242185057.91449725680432.631365959
2185063.48301944680482.748065669 2185189.1725203680642.644202837
#Sta/Elev= 30
       0 1716.31    37.6  1713.8    42.8 1713.22      57 1709.74    68.9  1708.1
    92.6 1706.57   108.1 1705.06   124.9 1704.14   128.9 1703.68  133.41 1702.29
   136.9 1700.82     141 1700.34   148.2 1700.82     153 1702.28   157.1 1703.09
   184.8 1704.16   209.4 1703.86   214.5  1704.2   223.6 1705.57   234.9 1706.43
   268.9 1710.54   289.7 1714.12   295.9 1715.61   306.1 1720.58   311.2  1722.1
   316.3 1722.93     341 1723.85   367.1  1723.9   372.2 1724.54   374.1 1725.55
#Mann= 4 ,-1,0
       0      .1       0  133.41    .045       0     153      .1       0
  350.71     .05       0
Bank Sta=133.41,153
XS Rating Curve= 0 ,0
Exp/Cntr(USF)=0,0
Exp/Cntr=0.3,0.1

Type RM Length L Ch R = 1 ,16231   ,366.5,362.6,358.3
XS GIS Cut Line= 4
2184794.17441305680624.0376013442184955.60674638680657.890320085
2185004.13677233680660.5124495662185149.49051778680710.706941414
#Sta/Elev= 30
       0 1748.84       2  1748.7       6 1747.33    14.3 1743.06    43.2 1732.98
    55.2 1729.62    83.8 1720.28   116.5 1709.37   134.4 1702.83   141.2 1701.54
   165.5  1701.3   169.5 1700.62  180.01 1697.37   189.5 1696.37   193.6  1696.6
   195.9 1697.36   201.6 1699.36   205.6 1700.04   230.5 1699.65   243.2 1701.43
     255 1702.12   260.1 1703.05   264.4 1704.81     277 1713.88   285.5 1718.86
   289.8 1720.47     294 1721.35   310.9 1722.88   361.7  1724.9   367.3 1726.23
#Mann= 3 ,-1,0
       0      .1       0  180.01    .045       0   195.9      .1       0
Bank Sta=180.01,195.9
XS Rating Curve= 0 ,0
Exp/Cntr=0.3,0.1

Type RM Length L Ch R = 1 ,15869   ,133.5,141.1,145.7
XS GIS Cut Line= 4
 2184683.1806657680937.0464130532184823.90459462 680984.52724111
2184897.26984725680968.136556381 2185034.9750173681011.464195967
#Sta/Elev= 30
       0 1753.76       1 1752.85       4  1751.8    13.7 1750.63    16.7 1749.27
    25.4 1743.72    35.6 1738.12    51.7 1730.83    64.4 1726.52    89.7 1718.36
   105.1 1715.06   123.5 1708.06     157 1696.98   168.3 1695.03   181.6 1694.54
   185.7  1693.5   189.91691.292   193.9 1690.14     198 1690.03   202.1 1690.16
  206.47 1691.29   223.6 1698.62   230.9 1700.96   256.1 1704.82   272.9 1705.96
   285.4 1707.64   303.4 1711.35   344.9 1721.26   356.7 1725.18   368.1 1726.82
#Mann= 3 ,-1,0
       0      .1       0   189.9    .045       0  206.47      .1       0
Bank Sta=189.9,206.47
XS Rating Curve= 0 ,0
Exp/Cntr=0.3,0.1

Type RM Length L Ch R = 1 ,15728   ,266.4,254.7,240.5
XS GIS Cut Line= 3
2184653.42350143681056.1912593672184934.81970317  681129.9908098
2185039.24175794681123.848550434
#Sta/Elev= 30
       0 1753.93       7 1749.91    19.4 1744.98    31.8 1740.84    40.1 1737.43
    48.9 1735.83    73.1 1727.05    85.5 1721.95   114.5 1711.87   122.8 1707.34
   135.2 1701.73   147.6 1694.82   151.7 1693.79   193.1 1692.75   197.2 1691.96
   206.21689.055   209.6 1688.15   213.7    1688   217.9 1688.27   221.1 1689.05
   222.6 1689.59   234.4 1697.09   242.7 1699.96   279.9 1703.23   292.3 1705.09
   304.3  1707.4   323.2 1712.14   364.4 1719.53   380.4 1723.79   395.5 1725.86
#Mann= 3 ,-1,0
       0      .1       0   206.2    .045       0   221.1      .1       0
Bank Sta=206.2,221.1
XS Rating Curve= 0 ,0
Exp/Cntr=0.3,0.1

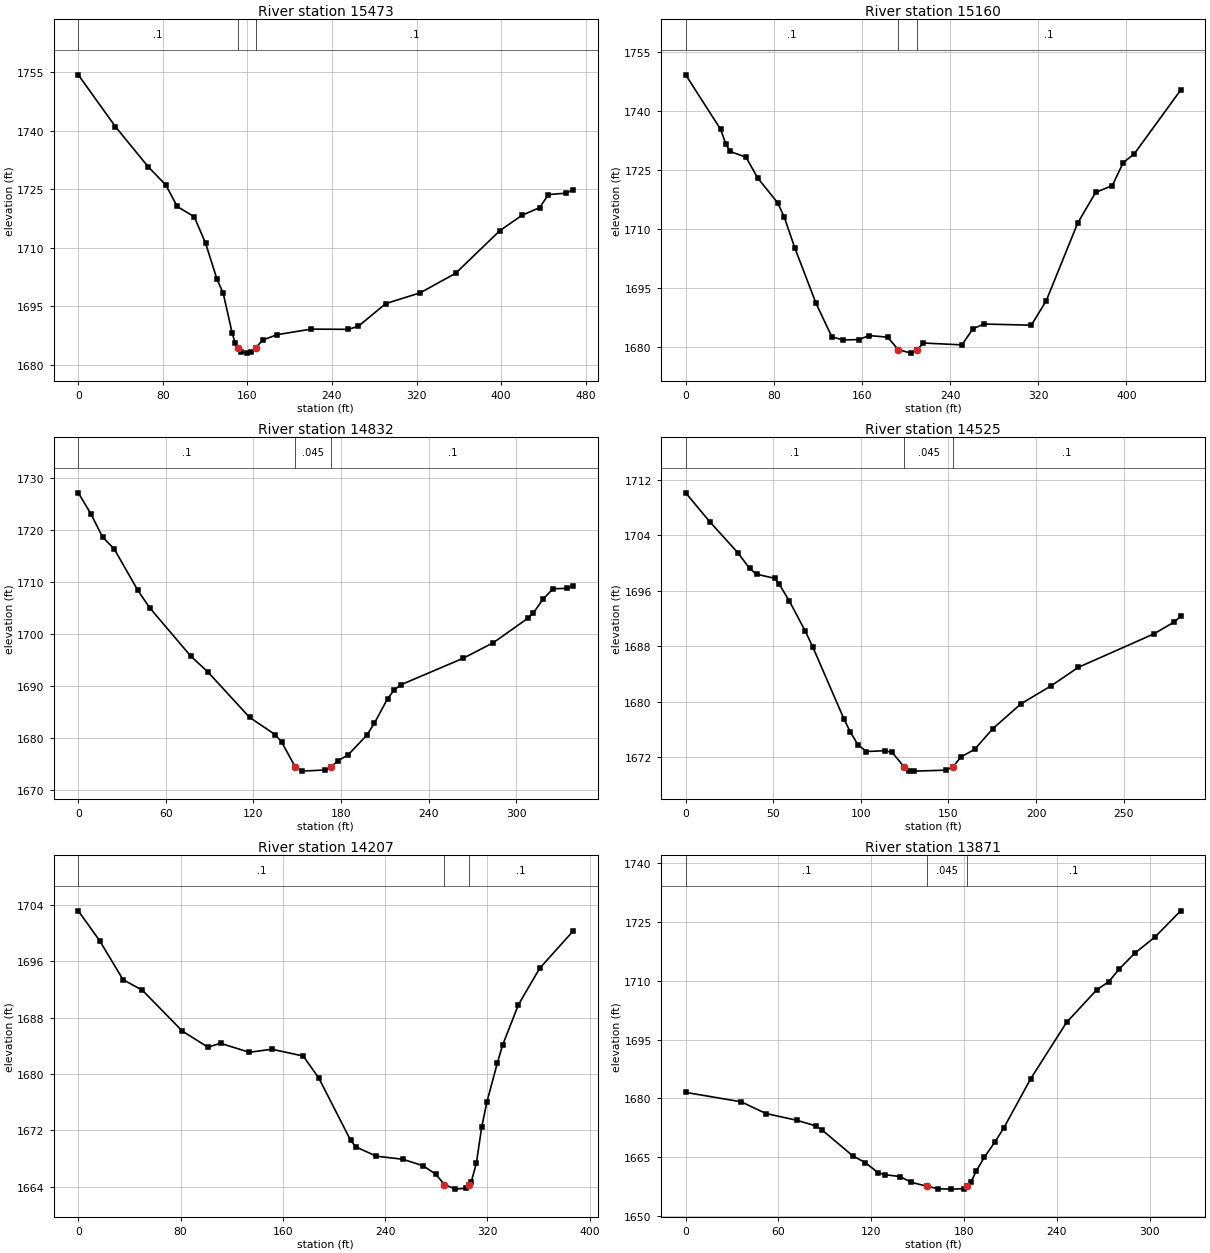
Type RM Length L Ch R = 1 ,15473   ,315.2,313.3,310.7
XS GIS Cut Line= 3
2184662.66259558681449.327586947 2184801.7787464681324.018049957
2185070.71249857681242.267633044
#Sta/Elev= 30
       0 1754.28    35.2 1740.98      66 1730.77    82.8 1726.07    93.6 1720.56
   109.7 1717.93   120.5  1711.1   131.2 1701.94   137.1 1698.35   145.6 1688.11
   148.5 1685.58  150.96 1684.22   154.1 1683.39   159.8 1683.01   163.5  1683.2
   167.71684.252   174.3 1686.35   188.2 1687.74   220.3 1689.16   255.6  1689.1
     265  1689.9   290.8 1695.68   323.5 1698.46     357 1703.46   398.8 1714.37
   419.7  1718.3   436.4 1720.26   444.8 1723.62   461.5 1723.97   468.3 1724.86
#Mann= 3 ,-1,0
       0      .1       0  150.96    .045       0   167.7      .1       0
Bank Sta=150.96,167.7
XS Rating Curve= 0 ,0
Exp/Cntr=0.3,0.1

Type RM Length L Ch R = 1 ,15160   ,318.1,328,327.8
XS GIS Cut Line= 4
2184849.87036214681666.8749231572184994.95670221681569.621208456
 2185060.7899433681483.4458320542185193.98273873681384.202796357
#Sta/Elev= 30
       0 1749.28    31.7 1735.42    36.5 1731.65    40.4 1729.77    54.8  1728.3
    65.4 1723.02    83.6 1716.68    89.5 1713.05    99.1  1705.2   118.3 1691.14
   132.6 1682.64   142.4 1681.82   156.9  1681.9   166.5 1682.92   183.3 1682.53
  192.82 1679.37   204.4 1678.46   210.2 1679.38   215.8 1681.03   250.7 1680.56
   260.8  1684.7   270.9 1685.86   313.7 1685.57   327.2 1691.79   355.8 1711.59
   372.1 1719.38   387.1 1721.07   397.1 1726.94   407.1 1729.17   449.2  1745.4
#Mann= 3 ,-1,0
       0      .1       0  192.82    .045       0   210.2      .1       0
Bank Sta=192.82,210.2
XS Rating Curve= 0 ,0
Exp/Cntr=0.3,0.1

Type RM Length L Ch R = 1 ,14832   ,307.6,306.2,303
XS GIS Cut Line= 3
2184971.73380499681848.355004814 2185092.6100701 681833.46722685
2185284.48782997681731.425720468
#Sta/Elev= 30
       0 1727.06     8.5 1723.09    16.6 1718.59    24.6 1716.29    40.7 1708.39
    48.8 1705.04      77 1695.74    88.8 1692.68   117.3 1683.98   134.9 1680.66
   139.4  1679.2   148.5 1674.52     153 1673.66     169 1673.88  173.37 1674.52
   177.9 1675.66   184.7 1676.74   197.5 1680.51   202.8 1682.83   211.9 1687.58
   216.4 1689.21     221 1690.23   263.6 1695.31   284.3  1698.3     308    1703
   311.6 1703.95   318.3 1706.63   325.2 1708.65   334.6 1708.73   339.1 1709.17
#Mann= 3 ,-1,0
       0      .1       0   148.5    .045       0  173.37      .1       0
Bank Sta=148.5,173.37
XS Rating Curve= 0 ,0
Exp/Cntr=0.3,0.1

Type RM Length L Ch R = 1 ,14525   ,330.5,318.6,283.7
XS GIS Cut Line= 4
2185175.04576652682179.5508582032185240.19747614682105.807714345
2185295.09373457682067.5884451612185355.11963302681966.965330798
#Sta/Elev= 30
       0 1710.15    13.8 1705.96    29.9 1701.46    36.5 1699.22    40.5 1698.39
    50.7 1697.81    53.5 1696.92    59.2  1694.5    68.2 1690.21    72.6 1687.85
    90.3 1677.51    93.9 1675.64    98.4 1673.73   103.2 1672.78   113.5  1672.9
   117.9 1672.65   124.6 1670.57   127.5 1669.98   130.4 1669.95   148.5 1670.09
  152.68 1670.56   156.9 1671.97   164.9 1673.09   175.2 1676.06   191.4 1679.68
   208.7 1682.29     224 1684.93     267 1689.75   278.7 1691.47   282.5 1692.29
#Mann= 3 ,-1,0
       0      .1       0   124.6    .045       0  152.68      .1       0
Bank Sta=124.6,152.68
XS Rating Curve= 0 ,0
Exp/Cntr=0.3,0.1

Type RM Length L Ch R = 1 ,14207   ,311.6,336.4,356
XS GIS Cut Line= 4
 2185342.7873397682294.0297693442185450.24890063682214.281238152
2185402.27293741682007.3553808862185429.88573633  681976.8964484
#Sta/Elev= 30
       0 1703.12    16.7 1698.89      35 1693.37    50.2 1691.86    81.4 1686.08
   101.4 1683.81   111.3 1684.35   133.8 1683.08   151.4 1683.51     176 1682.55
   188.3 1679.39     213 1670.63   217.1 1669.68   233.1 1668.36     254 1667.92
   269.8    1667   279.8 1665.79   286.5 1664.33   295.1 1663.69   303.3 1663.82
   305.8 1664.33   307.4 1664.68   311.5  1667.4   315.6 1672.45   319.7 1676.04
   327.9 1681.58     332  1684.1   344.4 1689.83     361 1694.98   387.3 1700.28
#Mann= 3 ,-1,0
       0      .1       0   286.5    .045       0   305.8      .1       0
Bank Sta=286.5,305.8
XS Rating Curve= 0 ,0
Exp/Cntr=0.3,0.1

Type RM Length L Ch R = 1 ,13871   ,259,269.3,269
XS GIS Cut Line= 4
2185492.48299689682277.2696064642185614.99748888682288.319764265
2185682.92645578682261.5186436982185784.64332278682190.491672388
#Sta/Elev= 30
       0 1681.52    35.8 1679.13    51.9 1676.13      72 1674.39      84 1672.98
      88    1672   108.1 1665.31   116.2  1663.6   124.3 1661.07   128.6 1660.53
   138.7 1660.05   145.8 1658.59  156.24 1657.55   163.3 1656.93   171.6 1656.84
   180.2 1656.95   181.8 1657.57   184.5 1658.69     188  1661.5   193.1 1664.96
   200.1 1668.93   205.8 1672.51     223 1684.92   246.3 1699.37   265.9 1707.72
   273.5 1709.73   280.5 1713.04   290.3 1716.99   303.5 1721.16   320.1 1727.84
#Mann= 3 ,-1,0
       0      .1       0  156.24    .045       0   181.8      .1       0
Bank Sta=156.24,181.8
XS Rating Curve= 0 ,0
Exp/Cntr=0.3,0.1