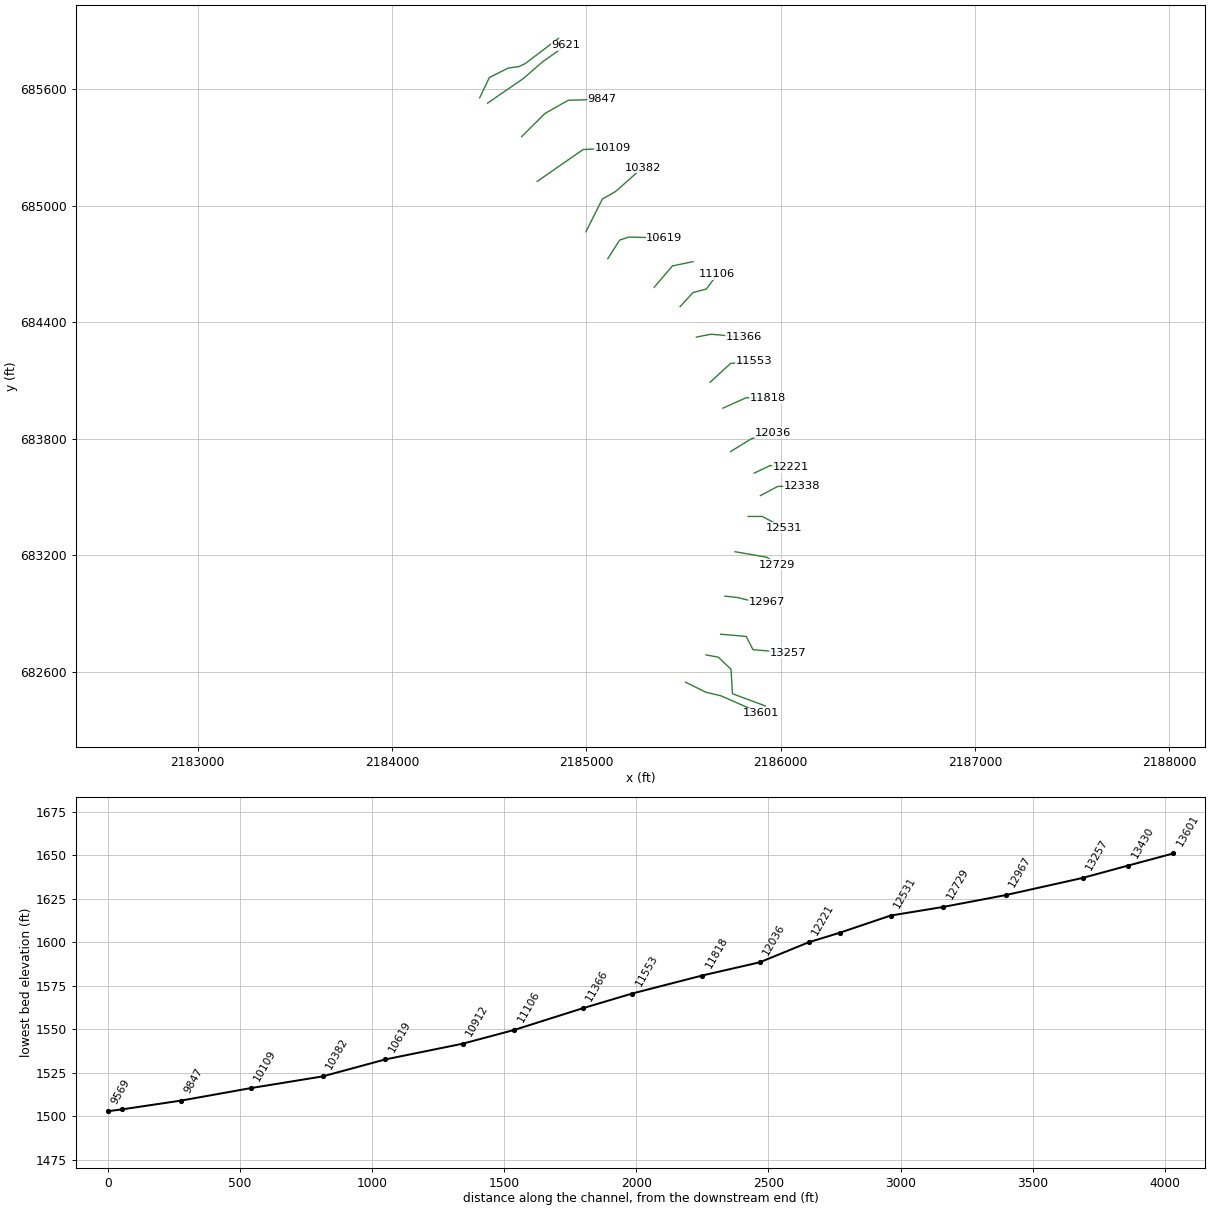
HEC-RAS study GRANDCMPRN.prj: GRANDCMPRN

--- GRANDCMPRN.g01 (geometry) --- (continued)

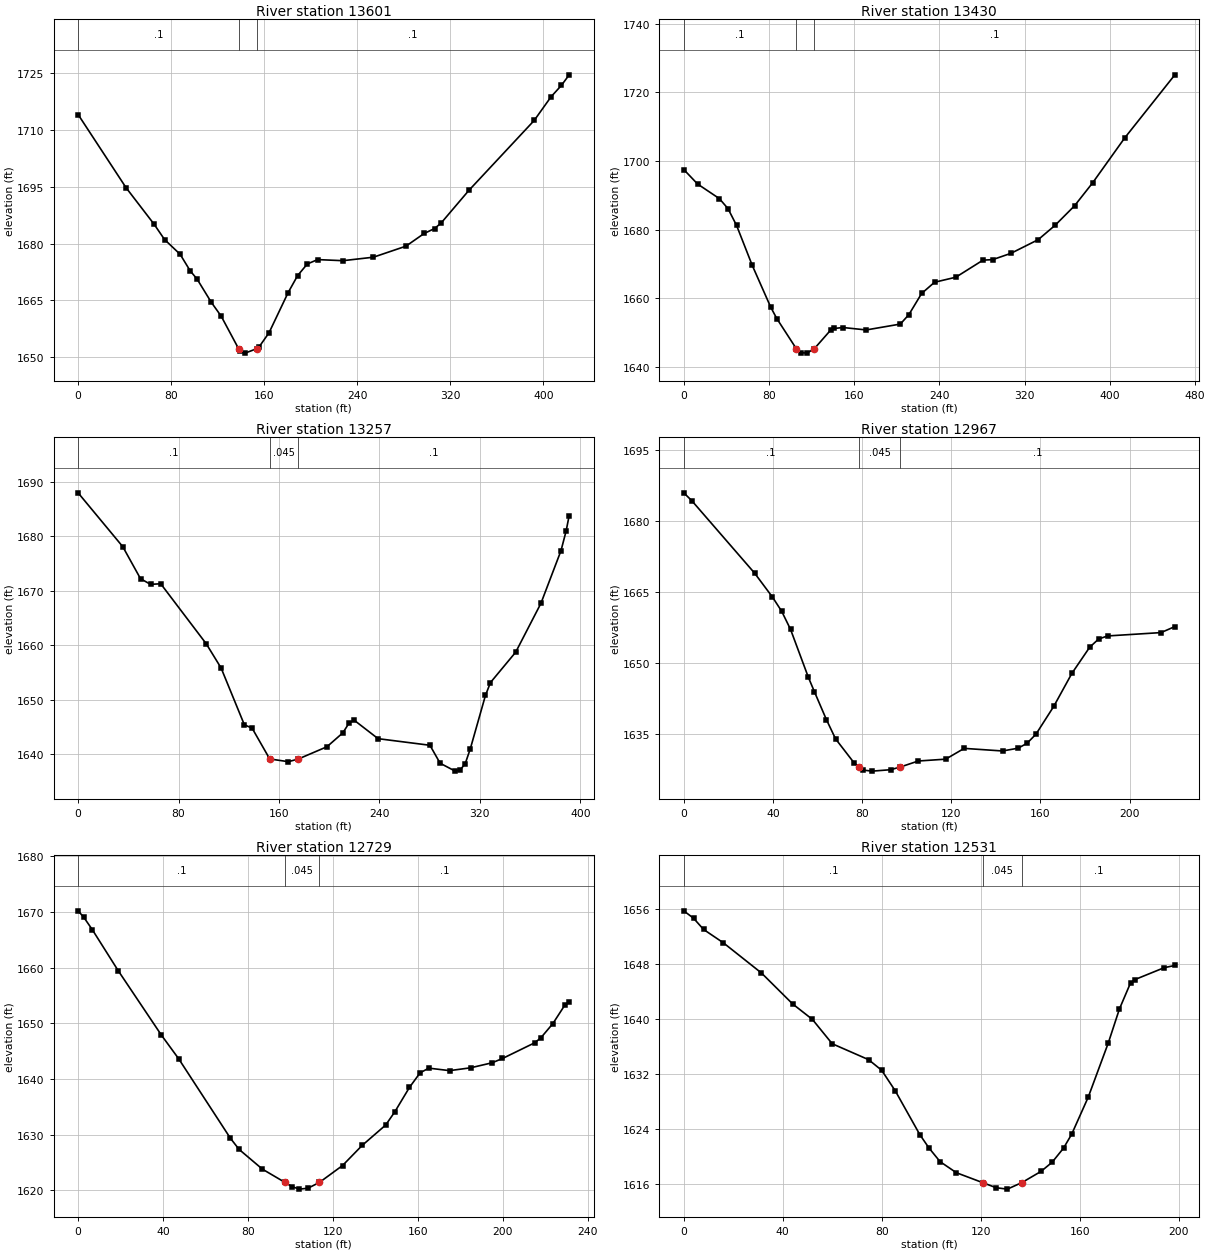
Type RM Length L Ch R = 1 ,13601   ,178.2,171.5,164.1
XS GIS Cut Line= 4
 2185509.4539601682547.3030621382185616.34284045682494.919273774
2185691.60783124682477.1928189082185898.31500266682386.510640232
#Sta/Elev= 30
       0 1714.12    41.2 1694.78    65.4 1685.08    74.3 1681.07    87.7 1677.16
    96.3 1672.81   102.3 1670.59   114.4 1664.51     123 1660.79  137.96 1652.19
   139.4 1651.54   143.5 1651.03   153.6 1652.21   155.8 1652.78   164.1 1656.41
   180.5 1667.02   188.7 1671.54     197  1674.6   205.9 1675.76   227.6 1675.47
   253.8 1676.39   281.8 1679.31   297.4 1682.66   306.4 1683.97   312.2 1685.49
   335.8 1694.03     392 1712.54   406.6 1718.84   415.4 1721.81   422.1 1724.61
#Mann= 3 ,-1,0
       0      .1       0  137.96    .045       0   153.6      .1       0
Bank Sta=137.96,153.6
XS Rating Curve= 0 ,0
Exp/Cntr=0.3,0.1

Type RM Length L Ch R = 1 ,13430   ,176.6,172.6,166.3
XS GIS Cut Line= 5
2185615.36420575682687.7216453112185678.63073866682676.055345581
2185744.12338709 682613.580158852185751.65792967682487.759745244
2185920.41067263682424.863640233
#Sta/Elev= 30
       0 1697.49      13 1693.27    33.4 1689.03    41.5 1686.12    49.6  1681.2
    64.3 1669.58    81.6 1657.44    87.3 1654.12  105.73 1645.29   109.9 1644.18
   115.6 1644.04   122.51645.308     138 1650.78     141 1651.21   149.4  1651.5
   171.3 1650.79   203.3  1652.5   211.3 1655.24   223.3 1661.41   235.4 1664.67
   255.4 1666.14   280.9 1671.11     290 1671.26   307.1 1673.09   332.7 1677.07
   348.6 1681.26   366.8 1686.92   383.9 1693.65   413.9 1706.68     461 1725.06
#Mann= 3 ,-1,0
       0      .1       0  105.73    .045       0   122.5      .1       0
Bank Sta=105.73,122.5
XS Rating Curve= 0 ,0
Exp/Cntr=0.3,0.1

Type RM Length L Ch R = 1 ,13257   ,269.4,290.4,301.6
XS GIS Cut Line= 4
2185690.66918834 682794.204146522185822.53726211682782.732320676
2185856.96186188682714.5081087512186038.62604435682699.332107888
#Sta/Elev= 30
       0 1687.93    35.6 1678.05    49.7 1672.19    57.7 1671.15    65.8 1671.26
   102.1 1660.24   113.9 1655.81   132.4 1645.41   138.6 1644.78   152.6 1639.14
   167.5 1638.64  175.46 1639.14   198.2 1641.38   210.8 1643.92     216 1645.79
     220 1646.22   238.9 1642.86   280.2 1641.65   288.3 1638.36   300.3 1636.91
   304.3 1637.14   308.3 1638.28   312.4 1641.04   324.4 1650.78   328.4 1653.15
   348.5 1658.72   368.6 1667.68   384.6 1677.35   388.6 1680.88   391.1 1683.77
#Mann= 3 ,-1,0
       0      .1       0   152.6    .045       0  175.46      .1       0
Bank Sta=152.6,175.46
XS Rating Curve= 0 ,0
Exp/Cntr=0.3,0.1

Type RM Length L Ch R = 1 ,12967   ,236.9,237.8,238.6
XS GIS Cut Line= 4
2185712.57185831682990.2629206972185776.71627952682983.199119514
2185843.77050121682966.7139801742185930.38711195682961.611091877
#Sta/Elev= 30
       0 1685.91     3.6 1684.25    31.8 1668.92    39.8 1663.86    43.9 1660.89
    47.9 1657.04    55.9  1646.9    58.6 1643.87      64 1637.95    68.1 1633.89
    76.3 1628.88   78.47 1627.97    80.5 1627.28    84.6 1627.07    92.8 1627.37
    97.21627.949   105.2 1629.21   117.5  1629.6   125.8 1631.88     143 1631.33
     150 1631.92     154 1632.96     158 1634.88     166 1640.78   174.1 1647.73
   182.1 1653.27   186.1    1655   190.1 1655.65   214.1 1656.36   220.3 1657.63
#Mann= 3 ,-1,0
       0      .1       0   78.47    .045       0    97.2      .1       0
Bank Sta=78.47,97.2
XS Rating Curve= 0 ,0
Exp/Cntr=0.3,0.1

Type RM Length L Ch R = 1 ,12729   ,201.4,197.9,193
XS GIS Cut Line= 3
2185765.52800967683218.9061786752185928.96737959683190.559322533
2185981.38828313683151.593238152
#Sta/Elev= 30
       0  1670.2     2.7 1669.03     6.7 1666.81    18.9 1659.44    39.2 1647.89
    47.3 1643.66    71.7 1629.36    75.8 1627.35    86.8  1623.8    97.2 1621.47
   100.7 1620.67   104.2 1620.22   108.2 1620.38  113.64 1621.43   124.5 1624.46
   133.7 1628.06   144.8 1631.73   149.1  1634.1     156 1638.49     161  1641.1
   165.1 1641.95   174.9  1641.5   184.8 1642.01   194.9 1642.91   199.8 1643.68
   214.9 1646.49   217.8 1647.37   223.5 1649.94   229.2  1653.3   231.2 1653.82
#Mann= 3 ,-1,0
       0      .1       0    97.2    .045       0  113.64      .1       0
Bank Sta=97.2,113.64
XS Rating Curve= 0 ,0
Exp/Cntr=0.3,0.1

Type RM Length L Ch R = 1 ,12531   ,185,192.7,198.2
XS GIS Cut Line= 3
2185832.15343399  683400.52251622185904.87184021683400.599632809
2186015.94869971683341.614337525
#Sta/Elev= 30
       0 1655.69       4  1654.6       8 1652.99      16 1651.05    31.4 1646.67
      44 1642.18      52 1639.93      60  1636.4    74.7 1634.09      80 1632.55
    85.5 1629.56    95.4 1623.22    99.1 1621.28   103.6 1619.29   110.2 1617.68
   120.91616.232   126.3  1615.5   130.8  1615.3  136.67 1616.25   144.4 1617.87
   148.9  1619.2   153.5 1621.25   156.8 1623.27   163.5 1628.66   171.6 1636.52
   176.1 1641.45   180.6 1645.24   182.4 1645.72   194.2 1647.44   198.5 1647.76
#Mann= 3 ,-1,0
       0      .1       0   120.9    .045       0  136.67      .1       0
Bank Sta=120.9,136.67
XS Rating Curve= 0 ,0
Exp/Cntr=0.3,0.1

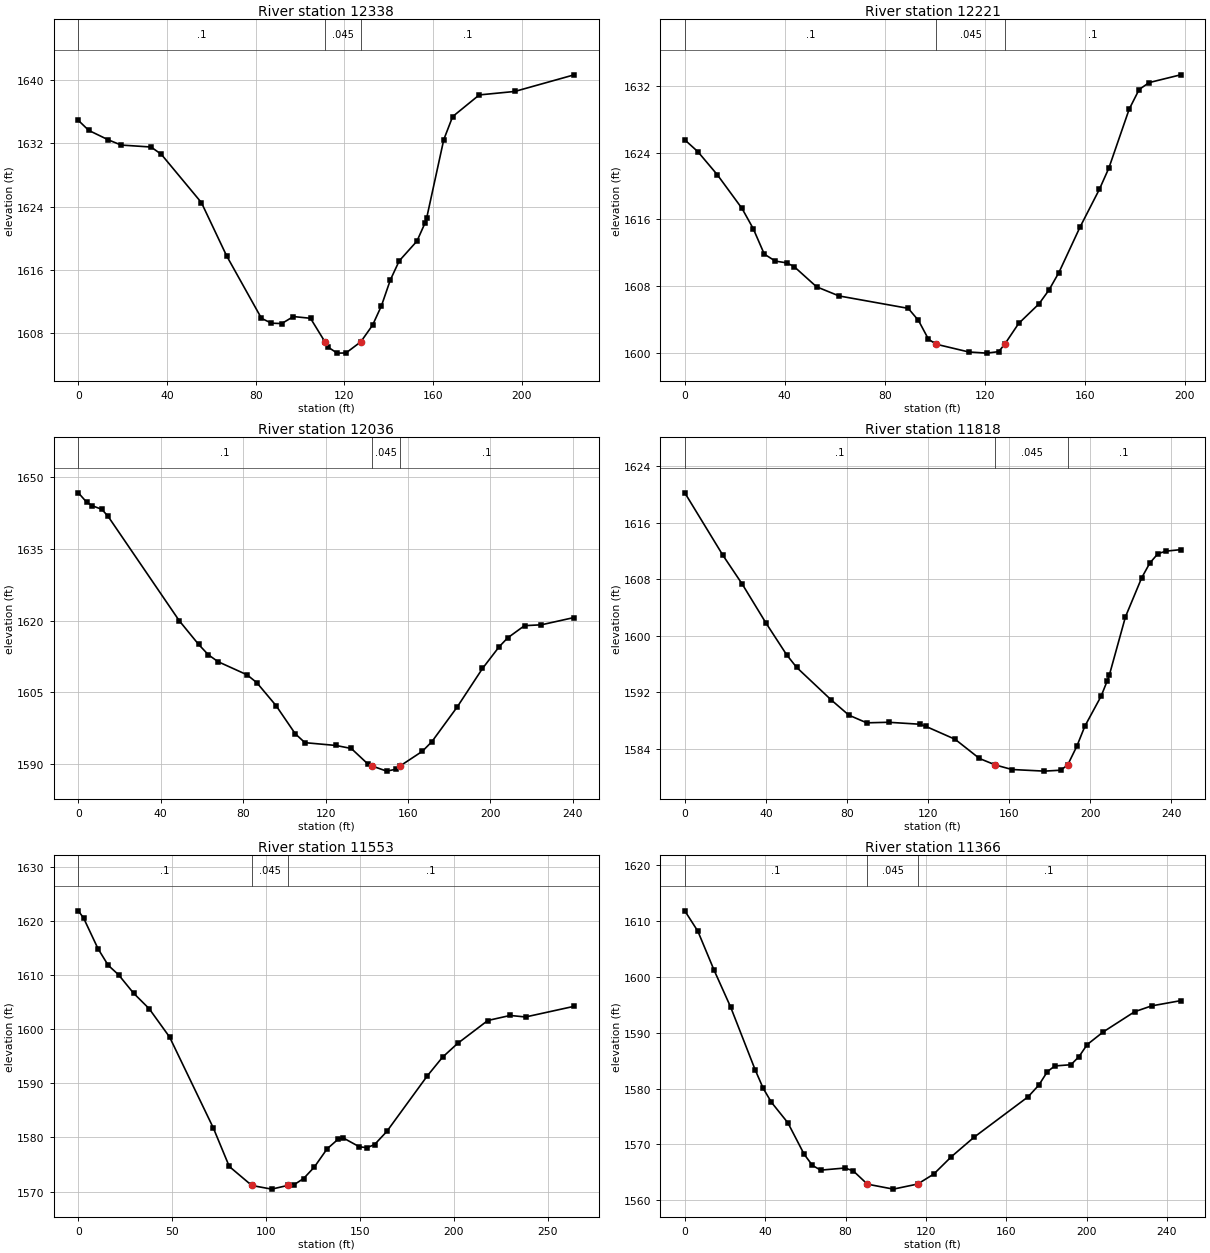
Type RM Length L Ch R = 1 ,12338   ,121.4,117.2,114.8
XS GIS Cut Line= 3
2185895.14830466683507.8063456722185984.08756503683554.871678413
2186106.99380244683559.239241677
#Sta/Elev= 30
       0 1634.93     4.7 1633.66    13.6 1632.45    19.3  1631.8    32.8 1631.55
    37.4 1630.63    55.5  1624.5    66.9 1617.73    82.6 1609.81    87.1  1609.2
    91.7 1609.15      97 1610.04   104.7 1609.82  111.26 1606.81   112.7 1606.15
   116.7  1605.4   120.7 1605.42   127.4 1606.84   132.7 1608.95   136.7 1611.41
   140.7 1614.68   144.7  1617.1   152.7 1619.61   156.4 1621.94   157.1 1622.56
   164.8 1632.49   168.8 1635.41   180.8 1638.16   196.8  1638.6   223.6 1640.71
#Mann= 3 ,-1,0
       0      .1       0  111.26    .045       0   127.4      .1       0
Bank Sta=111.26,127.4
XS Rating Curve= 0 ,0
Exp/Cntr=0.3,0.1

Type RM Length L Ch R = 1 ,12221   ,169.1,185.5,190.3
XS GIS Cut Line= 3
2185863.45162987683623.6154169032185945.38845637683662.595072233
2186052.78138432683654.640040533
#Sta/Elev= 30
       0 1625.52     5.2 1624.11      13 1621.34    22.9 1617.29    27.4 1614.86
    31.8 1611.82    36.2 1610.98    40.7 1610.77    43.7 1610.33    52.7  1607.9
    61.7  1606.8    89.4 1605.31    93.5 1603.86    97.5 1601.61  100.57 1601.01
   113.6 1600.08   120.8 1599.94   125.6 1600.12   128.11601.048   133.6  1603.5
   141.7 1605.84   145.7  1607.5   149.7 1609.61   158.1 1615.03   165.9 1619.59
   169.7 1622.15   177.8 1629.19   181.8 1631.56   185.8 1632.39   198.4 1633.32
#Mann= 3 ,-1,0
       0      .1       0  100.57    .045       0   128.1      .1       0
Bank Sta=100.57,128.1
XS Rating Curve= 0 ,0
Exp/Cntr(USF)=0,0
Exp/Cntr=0.3,0.1

Type RM Length L Ch R = 1 ,12036   ,218.6,217.6,211.7
XS GIS Cut Line= 4
 2185742.4280544683735.0833720972185846.37665495683798.975902719
2185899.59244415683819.9900099132185959.72045189683832.672213493
#Sta/Elev= 30
       0 1646.78       4 1644.84     6.7 1644.08    11.4 1643.32    14.4 1641.87
      49 1619.95    58.4 1614.98    63.1 1612.82    67.8 1611.37    81.9 1608.61
    86.6 1606.98      96 1602.14   105.3 1596.25     110 1594.38   125.1 1593.79
   132.5 1593.16   140.5 1589.93   142.6 1589.48   149.7 1588.41   154.1  1588.8
  156.16 1589.48     167 1592.57   171.6 1594.57   183.9 1601.85   196.2 1609.94
   204.3  1614.5   208.4 1616.35   216.6 1618.92   224.8  1619.1   240.7 1620.63
#Mann= 3 ,-1,0
       0      .1       0   142.6    .045       0  156.16      .1       0
Bank Sta=142.6,156.16
XS Rating Curve= 0 ,0
Exp/Cntr=0.3,0.1

Type RM Length L Ch R = 1 ,11818   ,234.4,264.7,274.8
XS GIS Cut Line= 3
2185702.39336702683958.033870889 2185821.3183051684011.613900056
2185935.32990812684009.726903289
#Sta/Elev= 30
       0 1620.24    18.8 1611.39    28.3 1607.32      40 1601.81    50.2 1597.31
    55.1 1595.53    72.1 1590.93    80.9 1588.75    89.7 1587.66   100.5 1587.74
     116 1587.46   118.7 1587.18   133.3 1585.33   145.3 1582.61  153.19 1581.69
   161.3 1581.05   177.3 1580.82   185.3 1580.95  188.78 1581.68   193.3 1584.33
   197.3  1587.2   205.3 1591.44   208.2 1593.53   209.3 1594.37   217.3 1602.68
   225.3  1608.2   229.3 1610.29   233.3 1611.62   237.3 1611.98   244.5 1612.19
#Mann= 3 ,-1,0
       0      .1       0  153.19    .045       0  188.78      .1       0
Bank Sta=153.19,188.78
XS Rating Curve= 0 ,0
Exp/Cntr=0.3,0.1

Type RM Length L Ch R = 1 ,11553   ,200.5,187.6,174.4
XS GIS Cut Line= 3
2185636.46747872684091.3097988372185741.85809429684188.534746856
2185861.96408704684200.728181337
#Sta/Elev= 30
       0 1621.83     2.8  1620.5    10.5 1614.83    15.9 1611.78    21.4 1610.04
    29.4 1606.64    37.7 1603.78    48.6 1598.54    71.9 1581.76    80.4 1574.65
   92.41 1571.14     103 1570.47   111.5 1571.15   114.8 1571.26     120 1572.43
   125.7 1574.54   132.5  1577.9   138.4 1579.69   141.1 1579.92   149.7 1578.28
   153.8 1578.12   157.8  1578.7   164.3 1581.11   185.9 1591.38     194 1594.82
     202 1597.35   218.1 1601.59     230 1602.52   238.2 1602.24   264.1 1604.21
#Mann= 3 ,-1,0
       0      .1       0   92.41    .045       0   111.5      .1       0
Bank Sta=92.41,111.5
XS Rating Curve= 0 ,0
Exp/Cntr=0.3,0.1

Type RM Length L Ch R = 1 ,11366   ,249.7,259.9,263.3
XS GIS Cut Line= 3
2185565.82363249684324.3611066242185642.01670721684338.964960349
2185810.50526916 684323.49584997
#Sta/Elev= 30
       0 1611.82     6.5 1608.17    14.6 1601.17    22.8  1594.6      35 1583.37
      39 1580.05    43.1 1577.54    51.3 1573.86    59.4 1568.23    63.5 1566.24
    67.6 1565.38    79.7 1565.76    83.8 1565.26   90.88 1562.87   103.8 1561.98
   115.9 1562.89   123.9 1564.67   132.7 1567.79     144 1571.28   170.9 1578.52
   176.2  1580.6   180.5 1583.03   184.2 1584.04   192.2 1584.26   196.2  1585.7
   200.3 1587.87   208.3 1590.14   223.9 1593.75   232.4  1594.8   246.8 1595.73
#Mann= 3 ,-1,0
       0      .1       0   90.88    .045       0   115.9      .1       0
Bank Sta=90.88,115.9
XS Rating Curve= 0 ,0
Exp/Cntr=0.3,0.1

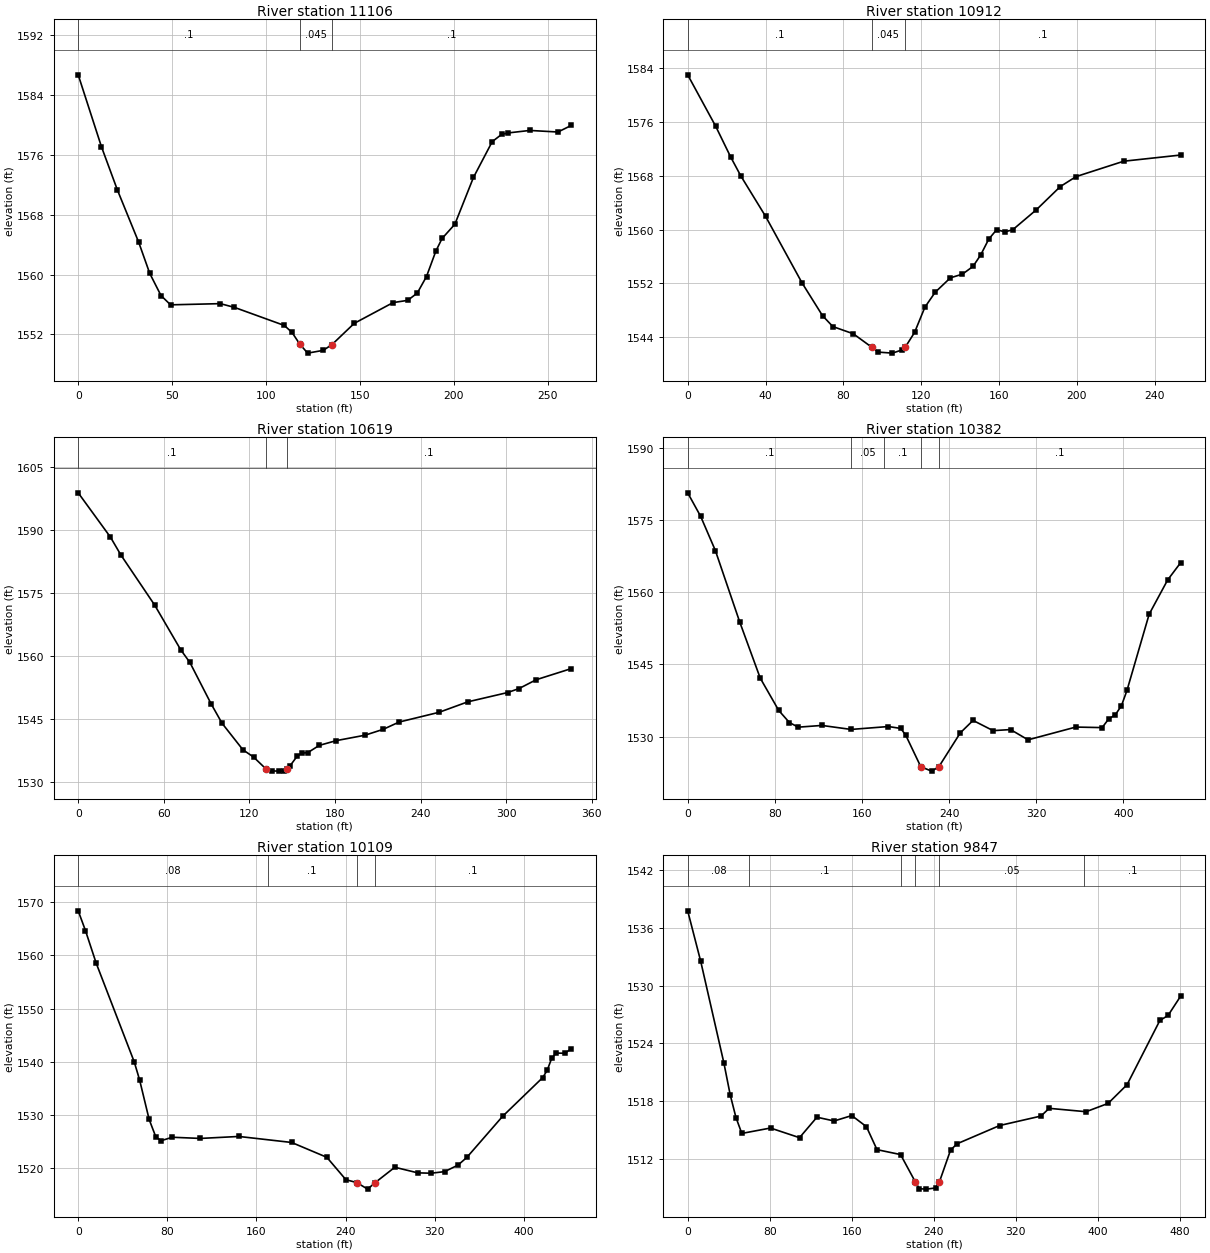
Type RM Length L Ch R = 1 ,11106   ,185.7,194.2,201.8
XS GIS Cut Line= 4
2185482.34782858684481.4512330732185548.46652496 684553.31671578
2185617.07220841684571.6921711792185673.40950145684646.809873551
#Sta/Elev= 30
       0 1586.72    12.4 1577.09    20.9  1571.3    32.2 1564.34    38.1 1560.16
    44.1 1557.19    49.2 1555.95    75.7 1556.11    83.2 1555.61   109.8 1553.19
   113.9 1552.25     1181550.698   122.2 1549.49   130.5 1549.86   135.2 1550.64
     147 1553.47   167.7 1556.25   175.5 1556.55   180.6 1557.53   185.5 1559.74
   190.5 1563.15   193.8 1564.83   200.6 1566.73   210.5 1572.99   220.5 1577.78
   225.5 1578.75   229.1 1578.95   240.5 1579.28   255.5 1579.07   262.6 1579.95
#Mann= 3 ,-1,0
       0      .1       0     118    .045       0   135.2      .1       0
Bank Sta=118,135.2
XS Rating Curve= 0 ,0
Exp/Cntr=0.3,0.1

Type RM Length L Ch R = 1 ,10912   ,300.5,292.7,287.2
XS GIS Cut Line= 3
2185348.60667819684580.3950019072185442.63808658684690.753146781
2185548.79803842684712.618133521
#Sta/Elev= 30
       0 1583.01    14.4 1575.35    22.1 1570.78    27.3 1567.97      40 1561.97
    58.8 1552.04    69.3 1547.18    74.6 1545.56    85.1 1544.49    94.51542.508
      98 1541.76   105.2 1541.61   110.3  1542.1   111.8 1542.49   116.6 1544.69
   121.9 1548.44   127.2 1550.67     135 1552.81   141.2 1553.36   146.6  1554.5
   150.6 1556.22   154.7 1558.56   158.8 1559.98   162.9 1559.65     167 1559.95
   179.2 1562.94   191.5 1566.39   199.6 1567.87   224.1 1570.16   253.4 1571.08
#Mann= 3 ,-1,0
       0      .1       0    94.5    .045       0   111.8      .1       0
Bank Sta=94.5,111.8
XS Rating Curve= 0 ,0
Exp/Cntr=0.3,0.1

Type RM Length L Ch R = 1 ,10619   ,234.2,237.3,239.6
XS GIS Cut Line= 4
2185110.28834442684727.9171274662185170.96620559684823.665091631
2185218.57845803684839.1698815222185400.75625194684834.847844193
#Sta/Elev= 30
       0 1598.86    22.6 1588.31    29.9 1584.07    53.6 1572.13    71.8 1561.52
    78.3 1558.46    93.2 1548.59   100.9 1543.95   115.5 1537.65     123 1535.91
   131.5 1533.14   135.7 1532.62   140.9 1532.57   144.1 1532.59  146.08 1533.13
   148.3 1533.73   153.6 1536.16   156.8 1536.87   160.9 1536.96     169  1538.7
     181 1539.84     201 1541.12   213.8 1542.52     225 1544.26   253.1 1546.59
   273.1 1549.07   301.1 1551.29   309.1 1552.24   321.1 1554.34   345.7 1556.99
#Mann= 3 ,-1,0
       0      .1       0   131.5    .045       0  146.08      .1       0
Bank Sta=131.5,146.08
XS Rating Curve= 0 ,0
Exp/Cntr=0.3,0.1

Type RM Length L Ch R = 1 ,10382   ,270.8,272.5,273.2
XS GIS Cut Line= 4
2184997.34638135684866.5337723332185082.10649507  685034.9724243
2185149.78401921685073.6894495662185289.20184055685197.050993279
#Sta/Elev= 30
       0 1580.61    11.9 1575.72    25.4 1568.63    47.7 1553.83    66.6 1542.13
    83.6 1535.41    93.4  1532.9   101.5 1531.94   123.2  1532.3     150 1531.47
   184.3 1532.07   195.6 1531.68   200.2 1530.27     214 1523.73   223.9 1522.81
  230.46 1523.67   250.3 1530.76     262 1533.34   280.4 1531.22   296.4 1531.44
   312.5 1529.31   356.3 1531.96   380.5 1531.85   386.5 1533.64   392.6 1534.51
   398.2 1536.38   403.3 1539.56   423.7 1555.41   440.7 1562.53   452.7 1566.13
#Mann= 5 ,-1,0
       0      .1       0     150     .05       0     180      .1       0
     214    .045       0  230.46      .1       0
Bank Sta=214,230.46
XS Rating Curve= 0 ,0
Exp/Cntr=0.3,0.1

Type RM Length L Ch R = 1 ,10109   ,263.6,262.7,261.9
XS GIS Cut Line= 3
2184746.86510854685125.7764687772184983.15591162685290.069892411
2185137.80807494685297.314865526
#Sta/Elev= 30
       0 1568.37     6.5 1564.67    16.2  1558.5    50.3 1539.98    55.1  1536.6
    63.7 1529.15    69.8 1525.81    74.7 1525.18    84.4 1525.81   109.7 1525.59
   144.2 1525.96   191.6 1524.83   223.2 1522.04   240.3 1517.83   250.1 1517.29
   259.8 1516.06   266.5 1517.27   284.2 1520.17   304.8 1519.12   316.8 1519.05
   328.9 1519.35   340.9 1520.57   348.9 1522.03   380.9 1529.73     417 1537.03
     421  1538.4     425 1540.63     429 1541.64     437 1541.59   442.6 1542.48
#Mann= 4 ,-1,0
       0     .08       0     170      .1       0   250.1    .045       0
   266.5      .1       0
Bank Sta=250.1,266.5
XS Rating Curve= 0 ,0
Exp/Cntr=0.3,0.1

Type RM Length L Ch R = 1 ,9847    ,222.5,225.8,228.3
XS GIS Cut Line= 4
2184666.80514696685356.2255696442184786.00253735685475.150845027
 2184906.1733487685543.5837214222185080.49337272685548.717992325
#Sta/Elev= 30
       0 1537.74    12.7 1532.51    35.3 1521.99    41.5 1518.67    47.1 1516.33
    52.8 1514.68    80.8 1515.24   109.1 1514.24   126.1 1516.36   142.9 1515.97
   160.1 1516.53   174.4 1515.38   184.7    1513   207.7 1512.49   222.2 1509.64
   226.1 1508.95   232.9 1508.91   241.8 1509.03  245.58 1509.65   256.5 1512.96
   262.9 1513.61   304.4  1515.5   344.7 1516.48   352.7 1517.28   388.7 1516.93
   410.2 1517.79   428.7 1519.73   460.7 1526.38   468.7  1526.9   481.1 1528.92
#Mann= 6 ,-1,0
       0     .08       0      60      .1       0  208.38     .05       0
   222.2    .045       0  245.58     .05       0  386.67      .1       0
Bank Sta=222.2,245.58
XS Rating Curve= 0 ,0
Exp/Cntr=0.3,0.1

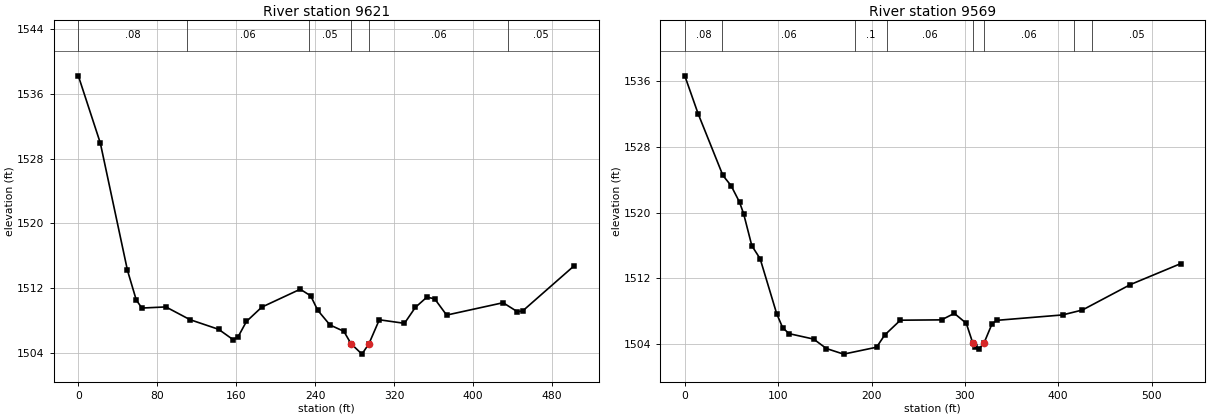
Type RM Length L Ch R = 1 ,9621    ,55.2,52,51.2
XS GIS Cut Line= 4
2184491.13364734685528.5555804182184675.65053122685655.663124988
2184774.90031721685742.0927222352184894.64508476685826.749267804
#Sta/Elev= 30
       0 1538.24    22.3 1529.91    49.8 1514.16    58.7  1510.5    64.4 1509.51
    88.7 1509.65     113 1508.08   142.1 1506.88   156.7 1505.61   161.6  1505.9
   170.3 1507.85   185.8 1509.62   224.8 1511.84   235.4 1511.02   242.5 1509.24
   254.9 1507.42     269 1506.63  276.23  1505.1   287.3 1503.81   294.41505.092
   304.9 1508.06   330.4 1507.62   341.4 1509.59   353.1 1510.86     361 1510.65
   373.1 1508.64   430.3 1510.17   444.9 1509.05   450.3 1509.17   502.3 1514.74
#Mann= 6 ,-1,0
       0     .08       0     110     .06       0  234.06     .05       0
  276.23    .045       0   294.4     .06       0  435.67     .05       0
Bank Sta=276.23,294.4
XS Rating Curve= 0 ,0
Exp/Cntr=0.3,0.1

Type RM Length L Ch R = 1 ,9569    ,42.1,42.1,40.7
XS GIS Cut Line= 6
2184450.85636823685556.3819919352184500.83924551685660.780630476
2184597.09512908685709.3063238452184653.57585415685717.261355545
2184686.19148412685733.1714189452184856.50018015685862.577521823
#Sta/Elev= 30
       0 1536.65    14.2 1532.06    40.8 1524.53    49.6 1523.28    58.6 1521.28
      63 1519.87    71.8 1515.97    80.7 1514.39    98.4 1507.71   104.9 1505.97
   111.8 1505.27     138 1504.61   151.7 1503.46   170.1 1502.78   205.4 1503.62
   214.1  1505.1   230.9 1506.91     275 1506.95   288.7 1507.74   301.5 1506.53
   308.4 1504.16   310.4  1503.6   314.8 1503.38  320.49 1504.13   329.1 1506.47
     334 1506.89   404.6 1507.55   425.9 1508.15   477.4 1511.25   531.1 1513.79
#Mann= 8 ,-1,0
       0     .08       0      40     .06       0  182.38      .1       0
  216.22     .06       0   308.4    .045       0  320.49     .06       0
  416.66      .1       0  436.66     .05       0
Bank Sta=308.4,320.49
XS Rating Curve= 0 ,0
Exp/Cntr=0.3,0.1