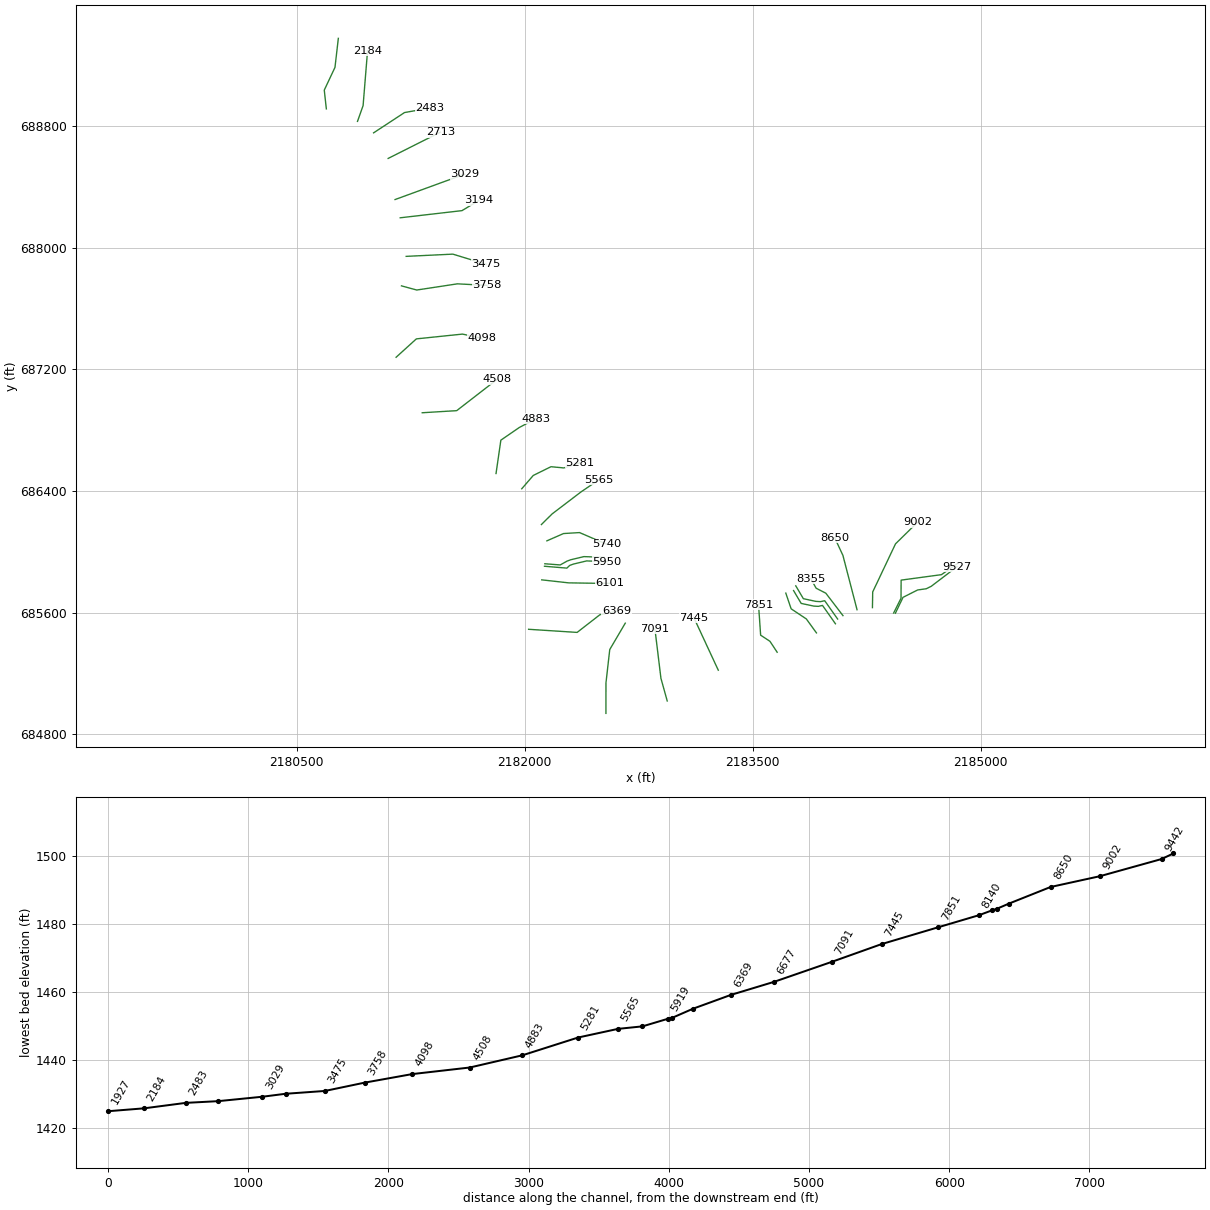
HEC-RAS study GRANDCMPRN.prj: GRANDCMPRN

--- GRANDCMPRN.g01 (geometry) --- (continued)

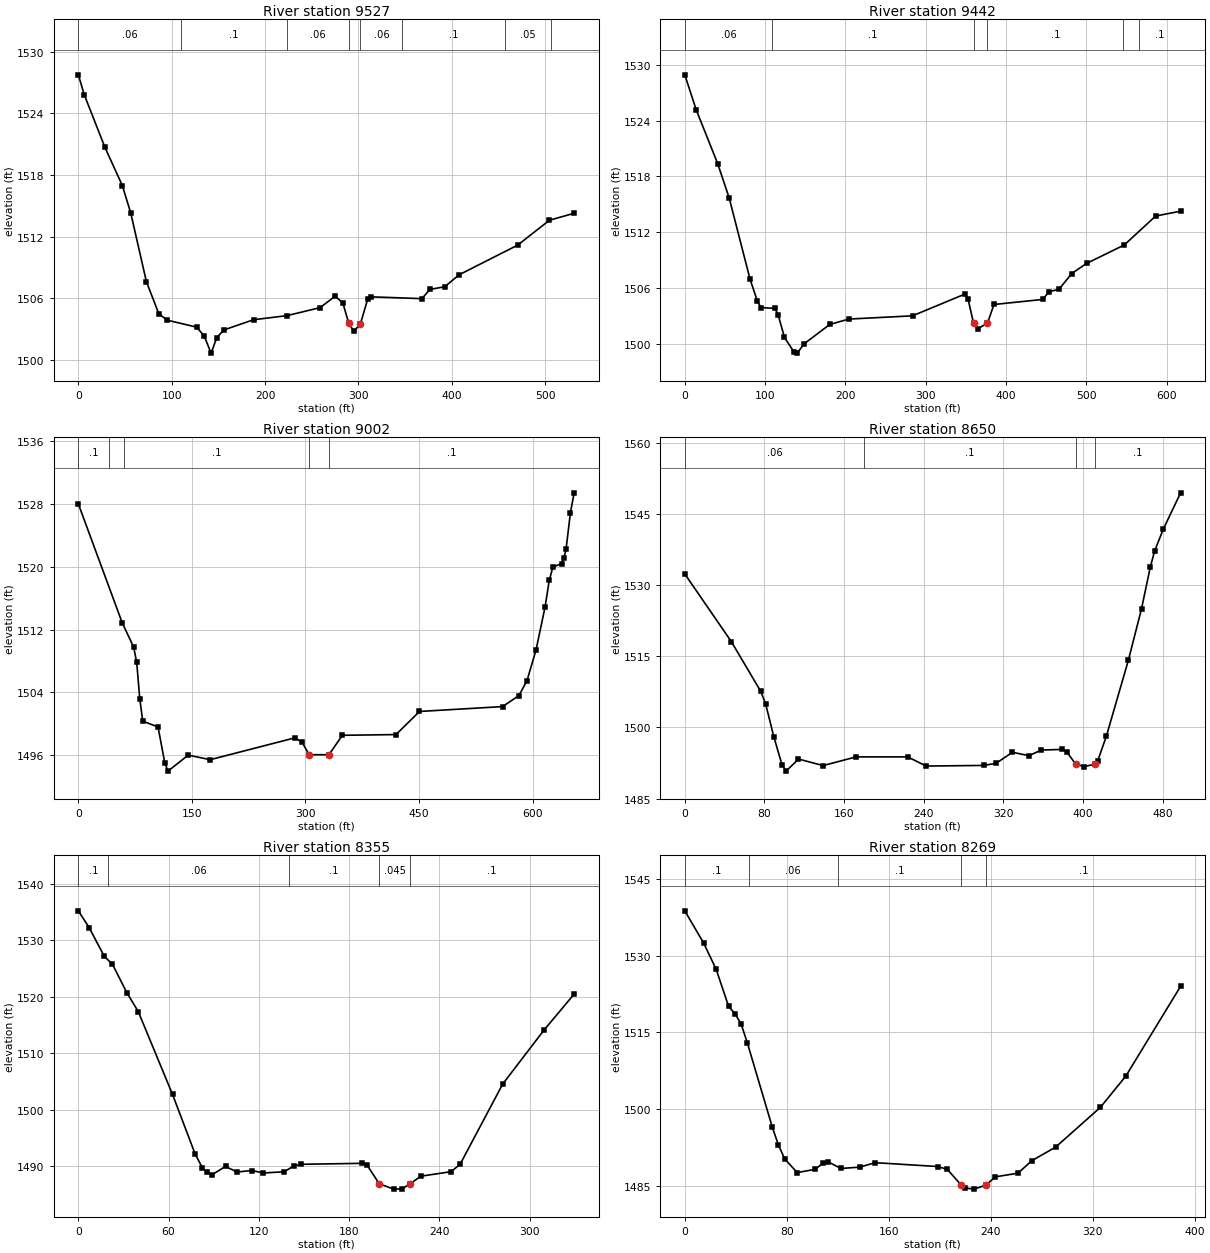
Type RM Length L Ch R = 1 ,9527    ,87.3,85.2,78.3
XS GIS Cut Line= 6
2184439.11462997685595.4466910572184489.09750725685699.845329598
2184585.35339082685748.3710229672184641.83411588685756.326054667
2184674.44974585685772.2361180672184844.75844189685901.642220946
#Sta/Elev= 30
       0 1527.74     6.4 1525.79    28.5 1520.68    47.1 1516.97    56.1 1514.31
    72.9 1507.62    86.2 1504.49    95.1 1503.87   126.6 1503.19   134.7 1502.35
   142.2 1500.66   148.3 1502.17     156 1502.92   187.7 1503.91   223.7 1504.31
     259 1505.09   275.1  1506.2   283.4 1505.53   289.7 1503.55   295.2 1502.78
  302.22 1503.52   310.1 1505.97   313.1 1506.14     368 1505.96   376.6 1506.86
   392.5 1507.12   407.8 1508.28   470.6 1511.17   504.6 1513.59   531.1 1514.27
#Mann= 8 ,-1,0
       0     .06       0     110      .1       0   223.7     .06       0
   289.7    .045       0  302.22     .06       0  347.09      .1       0
  456.66     .05       0  506.66      .1       0
Bank Sta=289.7,302.22
XS Rating Curve= 0 ,0
Exp/Cntr=0.3,0.1

Type RM Length L Ch R = 1 ,9442    ,430,439.6,454.6
XS GIS Cut Line= 5
2184427.49937368685596.5027098862184476.01589956685693.569693479
2184476.78355928685813.193973878 2184742.0675153685849.046368591
2184841.72132181685918.541803079
#Sta/Elev= 30
       0 1528.92    14.2 1525.16      41 1519.36    55.2  1515.7    81.2 1506.96
    90.2 1504.63    94.7  1503.9   112.1 1503.81   116.1 1503.15   124.1 1500.69
   136.1  1499.1   140.1    1499   148.1 1499.97   180.4 1502.08   204.1 1502.66
   283.5 1503.01   348.5 1505.34   352.7  1504.8  359.45 1502.22   364.8 1501.63
   376.8 1502.22   384.9 1504.23   445.5 1504.77   453.6 1505.61   465.7 1505.85
   481.8 1507.56   500.3 1508.65   547.2 1510.63   586.2 1513.74   617.3 1514.26
#Mann= 6 ,-1,0
       0     .06       0  108.52      .1       0  359.45    .045       0
   376.8      .1       0  545.84     .05       0  565.84      .1       0
Bank Sta=359.45,376.8
XS Rating Curve= 0 ,0
Exp/Cntr=0.3,0.1

Type RM Length L Ch R = 1 ,9002    ,338.3,351.6,363.9
XS GIS Cut Line= 4
2184288.03545982 685632.124352752184289.74159378685735.218003482
2184439.77432596686051.728008962 2184583.6714376686192.834334732
#Sta/Elev= 30
       0 1528.04    57.9 1512.89    73.1 1509.77    77.1 1507.83    81.1 1503.22
    85.1 1500.33   105.3 1499.59   114.1 1495.05   118.4 1493.96   145.1    1496
   174.2 1495.42   286.2 1498.21   295.6 1497.63   304.9 1496.05     331 1496.05
   348.7 1498.53   419.6 1498.62   450.6 1501.57   560.4 1502.19     582  1503.6
   592.6  1505.5   604.6 1509.43   616.4 1514.86     622 1518.27   626.8    1520
   638.3  1520.4   641.4 1521.15   644.2 1522.27     650 1526.94   654.9 1529.45
#Mann= 5 ,-1,0
       0      .1       0      40     .06       0      60      .1       0
   304.9    .045       0     331      .1       0
Bank Sta=304.9,331
XS Rating Curve= 0 ,0
Exp/Cntr=0.3,0.1

Type RM Length L Ch R = 1 ,8650    ,287.1,295.3,306.6
XS GIS Cut Line= 3
2184186.63616961685618.6217098872184093.78012051685975.648607112
2184039.38005806686092.874017733
#Sta/Elev= 30
       0 1532.32    46.8 1518.05    76.3 1507.59    81.2 1504.96    89.4 1498.05
    97.7  1492.1   101.8 1490.79   114.2 1493.33     139 1491.96   172.1 1493.79
   223.9 1493.79   242.4 1491.86   300.2 1491.99   312.6 1492.43   329.2 1494.76
   345.7 1494.04   358.1 1495.23   379.4 1495.36   383.8 1494.82   392.6 1492.28
   401.2 1491.75  412.51 1492.26   414.7 1492.89   423.5 1498.15   445.6 1514.14
   458.8 1524.97   467.6 1533.73     472 1537.18   480.8 1541.82   498.1 1549.41
#Mann= 4 ,-1,0
       0     .06       0     180      .1       0   392.6    .045       0
  412.51      .1       0
Bank Sta=392.6,412.51
XS Rating Curve= 0 ,0
Exp/Cntr=0.3,0.1

Type RM Length L Ch R = 1 ,8355    ,84.2,85.7,89.1
XS GIS Cut Line= 4
2184094.26475217 685579.487292022183981.19928435685727.255650348
2183917.39589575685759.8616243122183882.86422285685822.744599438
#Sta/Elev= 30
       0 1535.25     7.2 1532.27    17.2 1527.21    22.7 1525.77    32.3 1520.71
    39.8 1517.41    62.6 1502.72    77.7 1492.11    82.4 1489.75    85.4 1488.98
      89 1488.52    97.8 1489.96   105.4 1488.97   115.3 1489.24     123  1488.8
   136.8 1489.02   143.2 1490.05   148.2 1490.34   188.3 1490.51   191.7 1490.26
  200.04 1486.87   209.7 1485.94     215 1485.99   220.51486.871   227.6 1488.23
   247.7 1489.03   253.7 1490.34     282 1504.55   309.4  1514.1   329.5  1520.5
#Mann= 5 ,-1,0
       0      .1       0      20     .06       0     140      .1       0
  200.04    .045       0   220.5      .1       0
Bank Sta=200.04,220.5
XS Rating Curve= 0 ,0
Exp/Cntr=0.3,0.1

Type RM Length L Ch R = 1 ,8269    ,36.8,37.6,40.4
XS GIS Cut Line= 6
2184059.04751378685557.0742306562183974.08580869685677.574187146
2183946.47890238685671.5087210012183916.33718906685673.206776533
2183833.56346868 685690.960754412183783.62475919 685775.35293569
#Sta/Elev= 30
       0 1538.73    14.8 1532.44    24.6 1527.32    34.4 1520.07    39.5 1518.62
    44.2 1516.64    49.1 1512.94    68.6 1496.56    73.5 1493.01    78.4 1490.32
    88.2 1487.66   102.2 1488.29   108.3 1489.46   112.7 1489.72   122.5 1488.46
   137.2 1488.72   149.4 1489.59   198.4 1488.84     206 1488.28  216.86 1485.22
   219.5 1484.66     227 1484.43   236.3 1485.22   243.7 1486.83   261.4 1487.54
   272.2 1489.97   290.9 1492.62     326 1500.37   346.1 1506.52     389 1524.02
#Mann= 5 ,-1,0
       0      .1       0      50     .06       0     120      .1       0
  216.86    .045       0   236.3      .1       0
Bank Sta=216.86,236.3
XS Rating Curve= 0 ,0
Exp/Cntr=0.3,0.1

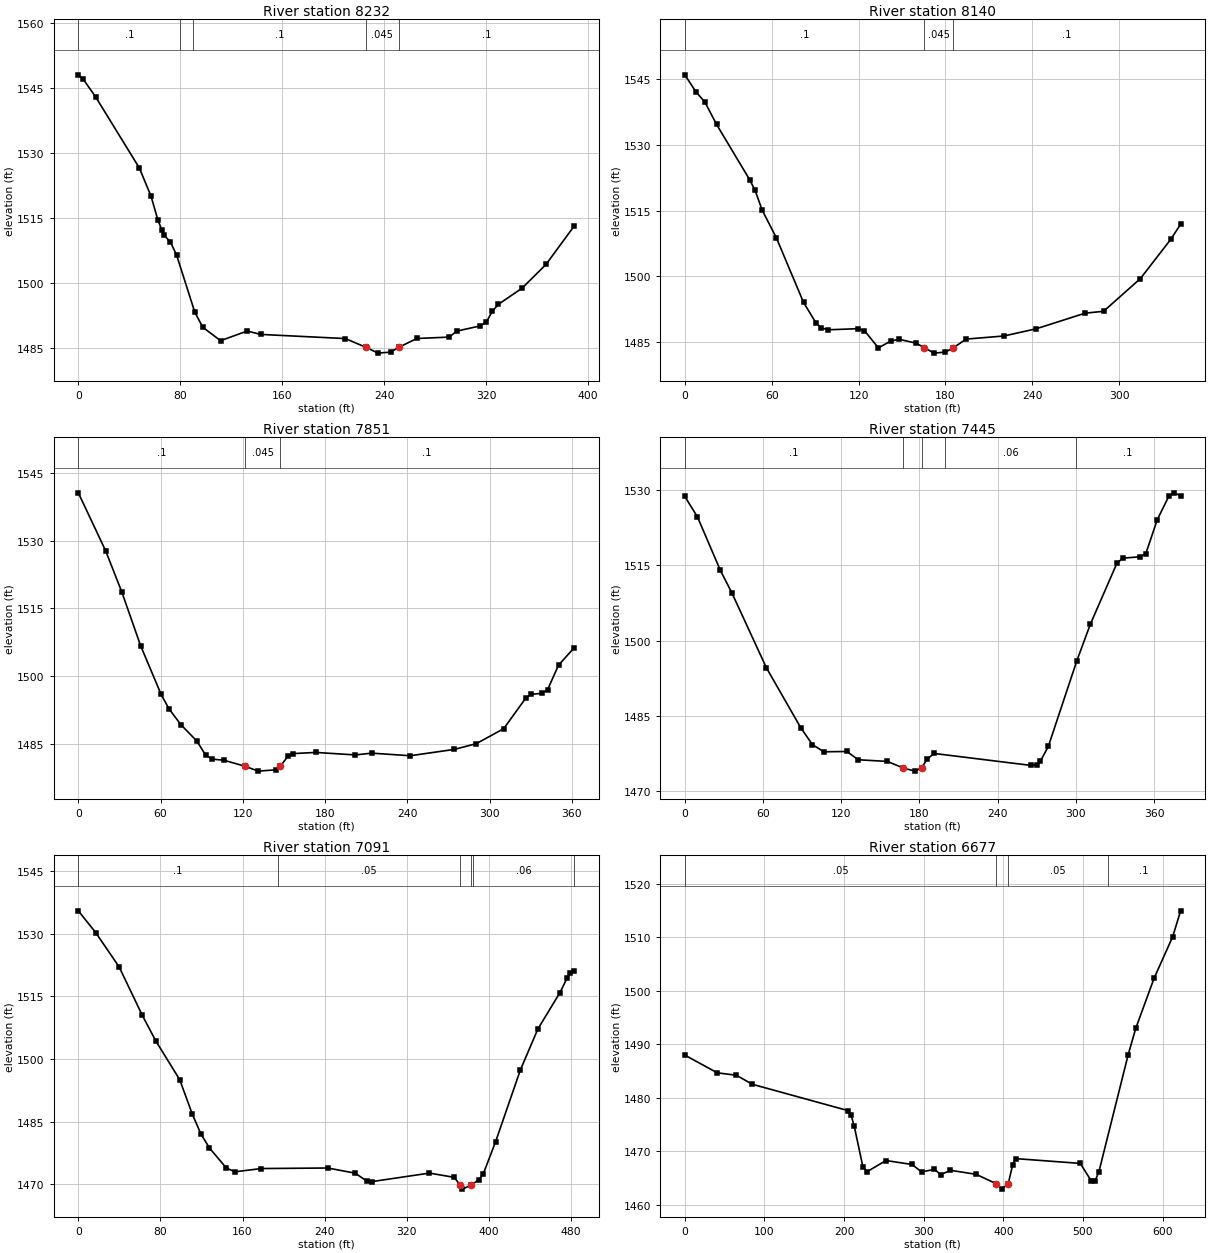
Type RM Length L Ch R = 1 ,8232    ,97.3,91.7,84.4
XS GIS Cut Line= 6
2184044.50056412 685526.093441832183959.53885902 685646.59339832
2183931.93195271685640.5279321752183901.79023939685642.225987707
2183819.01651901685659.9799655842183769.07780952685744.372146864
#Sta/Elev= 30
       0    1548     3.8 1547.01    13.6  1542.9    47.8 1526.58      57  1520.1
    62.5 1514.48    65.6 1512.23    67.4 1511.06    72.3 1509.47    77.1 1506.48
    91.4 1493.31    97.7 1489.85   111.6 1486.78   132.5    1489   143.1 1488.22
   209.6 1487.26   225.6 1485.25   235.2 1483.91   245.2 1484.15   251.3 1485.24
   265.6 1487.28   290.9  1487.6     297 1488.99   315.5 1490.19   320.1 1491.07
   324.8 1493.54   329.5 1495.14   348.1 1498.86   366.9 1504.33     389 1513.17
#Mann= 5 ,-1,0
       0      .1       0      80     .06       0      90      .1       0
   225.6    .045       0   251.3      .1       0
Bank Sta=225.6,251.3
XS Rating Curve= 0 ,0
Exp/Cntr=0.3,0.1

Type RM Length L Ch R = 1 ,8140    ,287.2,289.1,290.1
XS GIS Cut Line= 4
2183919.52164832685465.9388870542183852.85812354 685557.91265528
2183753.11224684685624.4036698552183718.09226452685727.507420245
#Sta/Elev= 30
       0 1545.93     7.6  1542.1    13.9  1539.7    21.9 1534.65    44.8 1522.02
    48.5 1519.62    53.4 1515.12    63.3 1508.74      82 1494.06    90.6  1489.4
    94.3 1488.25    99.2 1487.83   119.5 1488.08     124 1487.66   133.7  1483.7
   142.4  1485.3   148.1 1485.66   159.7 1484.78   165.5 1483.74   172.1 1482.51
   179.9 1482.75  185.35  1483.7   194.3 1485.71   220.3 1486.41   242.7 1488.06
   276.5 1491.62   289.2 1492.04   314.6 1499.49   335.7 1508.49   342.4 1511.89
#Mann= 3 ,-1,0
       0      .1       0   165.5    .045       0  185.35      .1       0
Bank Sta=165.5,185.35
XS Rating Curve= 0 ,0
Exp/Cntr=0.3,0.1

Type RM Length L Ch R = 1 ,7851    ,417,406,393.1
XS GIS Cut Line= 4
2183661.17691215685338.6079353532183613.64039224685410.707021483
2183552.41845982685450.8542589382183538.52583936685652.469776719
#Sta/Elev= 30
       0 1540.62    19.9 1527.79    31.8 1518.59    45.4 1506.79    60.3 1496.03
    66.1 1492.79    74.9 1489.24    86.4 1485.66    92.9 1482.52    97.7 1481.65
   106.5 1481.37   121.6 1480.06   131.2 1478.98   144.1 1479.27  147.25 1480.02
   152.8 1482.24   156.5 1482.86   173.2 1483.12     202 1482.57     214 1482.96
   242.1 1482.39   274.2 1483.79   290.2 1485.05   310.3 1488.38   326.3 1495.11
   330.3 1495.98   338.3 1496.22   342.3 1497.01   350.3 1502.45   361.7  1506.3
#Mann= 3 ,-1,0
       0      .1       0   121.6    .045       0  147.25      .1       0
Bank Sta=121.6,147.25
XS Rating Curve= 0 ,0
Exp/Cntr=0.3,0.1

Type RM Length L Ch R = 1 ,7445    ,356.9,353.9,347.9
XS GIS Cut Line= 2
 2183273.7657322685220.4030356572183113.55498974685565.367184284
#Sta/Elev= 30
       0  1528.7     9.7 1524.63    27.3 1513.97    36.1 1509.51    62.6 1494.59
    88.9 1482.68    97.9 1479.29   106.7 1477.86   124.3 1477.92   133.2 1476.27
   155.4 1475.94  167.74 1474.62   176.5 1474.01   181.7 1474.63   186.1 1476.49
   191.5 1477.52   265.5 1475.15   269.9 1475.26   272.8 1475.98   278.9 1478.93
   300.8 1496.01   311.2  1503.3   331.6 1515.44   336.1 1516.41   349.3 1516.69
   353.7 1517.32   362.5 1524.08   371.3 1528.72   375.2 1529.42   380.4 1528.85
#Mann= 5 ,-1,0
       0      .1       0  167.74    .045       0   181.7      .1       0
     200     .06       0     300      .1       0
Bank Sta=167.74,181.7
XS Rating Curve= 0 ,0
Exp/Cntr=0.3,0.1

Type RM Length L Ch R = 1 ,7091    ,416.3,414.5,408.9
XS GIS Cut Line= 3
2182937.86892411685018.0202634192182896.51029768685166.633496612
2182856.73066517685493.184192011
#Sta/Elev= 30
       0 1535.48    16.9 1530.28    39.7 1522.07    62.4 1510.41    75.4 1504.36
    98.8 1495.03   111.2 1486.69   119.5 1482.01   127.8 1478.66   144.4 1473.83
   152.8 1472.97   178.4 1473.74   243.1 1473.87   269.7 1472.64   281.7 1470.66
   285.8  1470.6   342.2 1472.65   366.4 1471.63  371.97 1469.82   374.4 1468.81
   383.1 1469.82   390.5 1471.08   394.6 1472.43   406.7 1480.18   430.8 1497.35
   447.8 1507.14   469.4  1515.9   476.5 1519.44   479.2 1520.47   483.2 1521.01
#Mann= 6 ,-1,0
       0      .1       0  194.26     .05       0  371.97    .045       0
   383.1     .05       0  384.26     .06       0  483.23      .1       0
Bank Sta=371.97,383.1
XS Rating Curve= 0 ,0
Exp/Cntr=0.3,0.1

Type RM Length L Ch R = 1 ,6677    ,315.2,307.2,296.7
XS GIS Cut Line= 4
2182534.63400458684936.4050133482182534.79033483685137.208950806
2182559.64907878685356.1793136592182661.72554009685529.864325771
#Sta/Elev= 30
       0 1487.97    40.8 1484.65    64.8  1484.2    84.8 1482.51   204.8 1477.59
   208.8 1476.74   212.8 1474.64   223.7 1467.03     229 1466.17   252.6 1468.25
   285.3 1467.51   297.4 1466.12   313.5  1466.6   321.5 1465.61   333.6 1466.42
   365.8 1465.67   391.3  1463.9     398  1462.9   406.1 1463.89   411.7 1467.44
   415.3 1468.61   496.6 1467.71   510.5 1464.41   515.1 1464.46   519.8 1466.04
   556.7 1488.01   566.2 1492.95   589.4 1502.39   612.6 1510.09   622.6 1514.95
#Mann= 4 ,-1,0
       0     .05       0   391.3    .045       0   406.1     .05       0
  531.18      .1       0
Bank Sta=391.3,406.1
XS Rating Curve= 0 ,0
Exp/Cntr=0.3,0.1

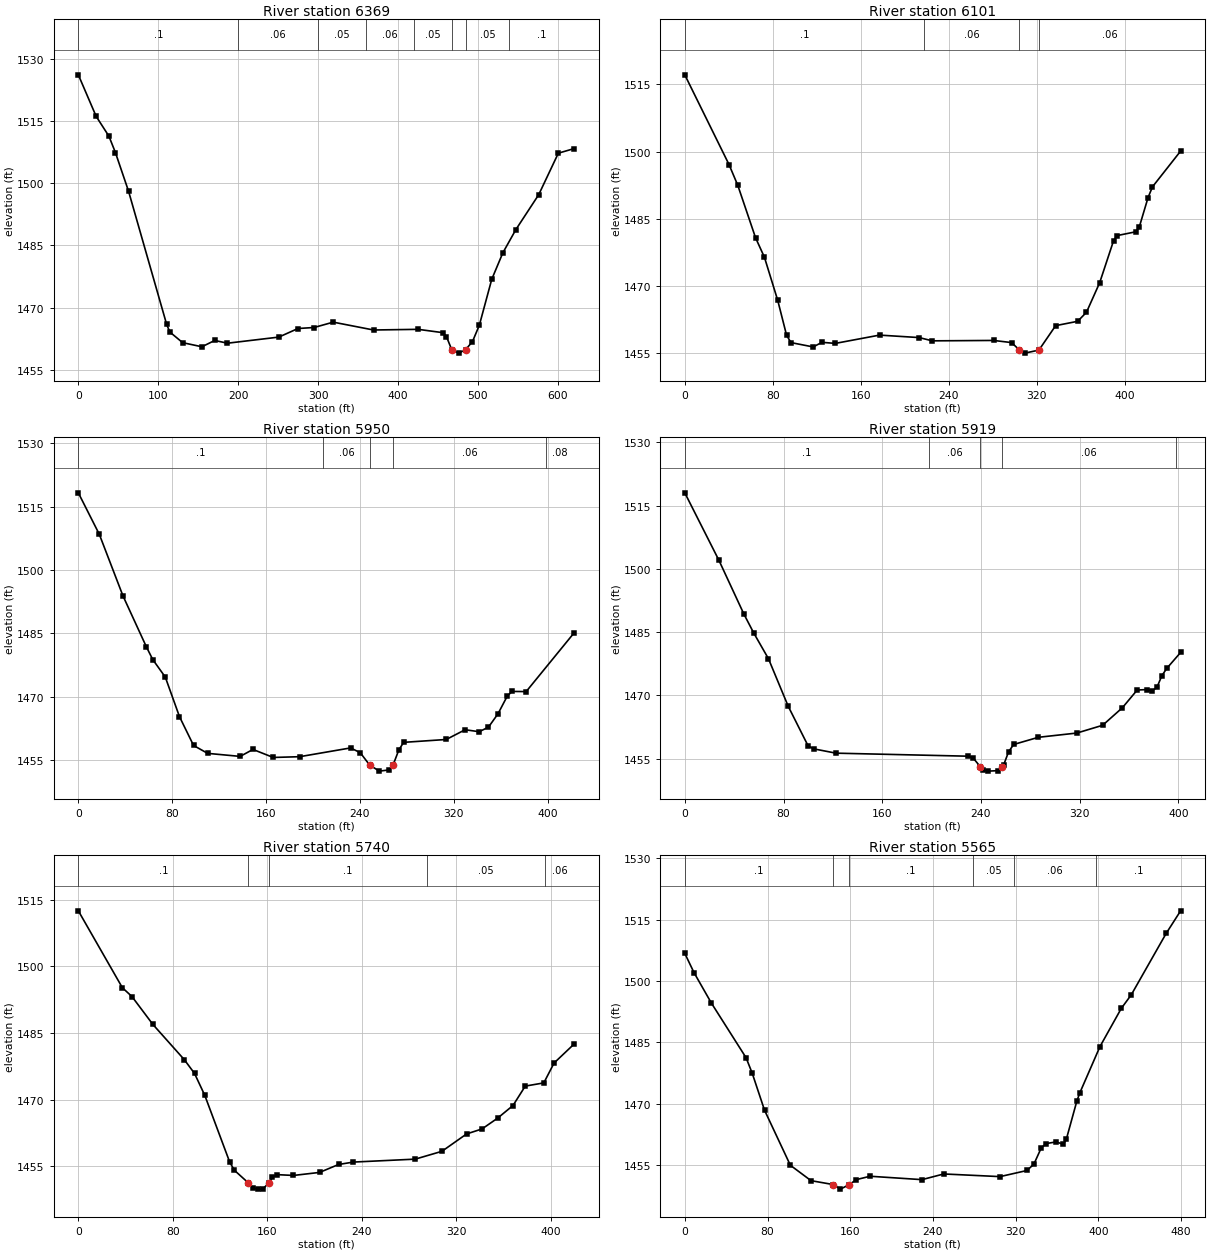
Type RM Length L Ch R = 1 ,6369    ,276,268.8,257.8
XS GIS Cut Line= 4
2182025.91782882685489.6062155592182345.11658156685469.139530842
2182494.44728192685585.1369112122182603.60107436685607.241953905
#Sta/Elev= 30
       0 1526.09    22.3 1516.09    38.3  1511.3    46.4 1507.37    62.8 1498.08
   110.5 1465.98   114.5 1464.15   130.5 1461.59   154.6  1460.6   170.6 1462.12
   186.6 1461.46   250.8 1462.93   274.8    1465   294.9 1465.24   318.9 1466.53
   369.3 1464.64     425  1464.8     456    1464   460.5 1463.06  467.17 1459.89
     476 1459.07   484.5 1459.91   493.1 1461.86   501.7  1465.8   517.2 1476.85
   531.1 1483.23   547.4 1488.83     576 1497.24   600.5 1507.22   620.3 1508.33
#Mann= 8 ,-1,0
       0      .1       0     200     .06       0     300     .05       0
  359.85     .06       0  419.85     .05       0  467.17    .045       0
   484.5     .05       0  538.94      .1       0
Bank Sta=467.17,484.5
XS Rating Curve= 0 ,0
Exp/Cntr=0.3,0.1

Type RM Length L Ch R = 1 ,6101    ,146.5,150,153.3
XS GIS Cut Line= 4
2182112.23497233685814.9007280022182288.86933545685795.116949493
2182461.23979212685792.4748454382182561.82522727685792.281027262
#Sta/Elev= 30
       0 1517.12    40.2  1497.1    48.2 1492.44    64.3 1480.78    72.4 1476.41
    84.5 1466.78    92.5 1459.03    96.5 1457.38   116.7 1456.41   124.7 1457.44
   136.8  1457.2     177 1459.05     213  1458.5     225 1457.77   280.7 1457.86
   297.1 1457.38   304.2 1455.71   309.1 1455.03  321.89 1455.71   337.1 1461.16
   357.1 1462.13   365.1 1464.14   377.1 1470.73   389.8 1480.15   393.1 1481.26
   409.9  1482.1   413.1 1483.15   421.1 1489.74   425.1 1492.13   450.7 1500.11
#Mann= 4 ,-1,0
       0      .1       0  217.74     .06       0   304.2    .045       0
  321.89     .06       0
Bank Sta=304.2,321.89
XS Rating Curve= 0 ,0
Exp/Cntr=0.3,0.1

Type RM Length L Ch R = 1 ,5950    ,31.7,31.8,31.7
XS GIS Cut Line= 6
2182130.37071021685904.3659839582182277.29888086685892.113525291
2182296.47541055685909.920302858 2182319.7611966685918.481253611
2182407.25906295685939.4738527982182541.03526609685934.616726879
#Sta/Elev= 30
       0 1518.29    17.9 1508.44      38 1493.89      58 1481.78    63.4 1478.78
    74.1 1474.62    86.2 1465.23    98.2 1458.41   110.2 1456.54   137.9 1455.82
   148.8 1457.47   166.1 1455.57   188.6 1455.75     232 1457.83   240.2  1456.7
   248.4 1453.72   256.6 1452.33   264.9 1452.62   268.11453.709   273.1 1457.35
   277.2 1459.15   313.5 1459.83   329.6 1462.14   341.6 1461.67   349.5 1462.76
   357.6 1465.92   365.6 1470.16   369.6 1471.22   381.6 1471.18   422.5 1485.12
#Mann= 5 ,-1,0
       0      .1       0  208.63     .06       0   248.4    .045       0
   268.1     .06       0  398.61     .08       0
Bank Sta=248.4,268.1
XS Rating Curve= 0 ,0
Exp/Cntr=0.3,0.1

Type RM Length L Ch R = 1 ,5919    ,180.9,178.9,176.1
XS GIS Cut Line= 6
2182132.57813425 685920.751069732182233.80925103685913.002245129
2182278.82142885685938.290719684 2182302.1072149685946.851670437
2182389.60508125685967.8442696242182523.38128439685962.987143705
#Sta/Elev= 30
       0 1518.03    27.7    1502    47.8 1489.33    55.8 1484.83    67.8 1478.69
    83.8 1467.42    99.9 1458.04   104.3 1457.33   122.5  1456.3   229.5 1455.58
   233.6 1455.18   239.4 1453.11   241.8 1452.27   245.9 1452.04   254.2 1452.16
  257.21 1453.08   258.3 1453.44   262.4 1456.63   266.5 1458.36   286.5 1460.06
   317.7 1461.07   338.6 1462.91   354.6 1467.07   366.6 1471.27   374.6 1471.38
   378.6 1471.05   382.6 1471.91   386.6 1474.67   390.6 1476.41   401.8 1480.18
#Mann= 5 ,-1,0
       0      .1       0  197.99     .06       0   239.4    .045       0
  257.21     .06       0  397.97     .08       0
Bank Sta=239.4,257.21
XS Rating Curve= 0 ,0
Exp/Cntr=0.3,0.1

Type RM Length L Ch R = 1 ,5740    ,166.8,174.8,182.7
XS GIS Cut Line= 4
2182146.04290662686071.5499850082182255.79397667686119.585939891
 2182361.1342853 686125.895019022182539.78860835686048.786157762
#Sta/Elev= 30
       0 1512.48    37.3 1495.17    45.4 1493.19    63.1 1486.92    89.7 1478.99
    98.4 1475.88   107.1 1470.94   128.2 1455.92   132.2 1454.07  143.87 1451.27
   148.2 1450.06   152.2 1449.84   156.2 1449.86   161.51451.285   164.3 1452.48
   168.3  1453.1   182.2 1452.92   204.3  1453.6   220.4 1455.39     233 1455.93
   285.3 1456.59   307.9 1458.35   328.8 1462.26   341.9 1463.39     355  1465.8
   368.1 1468.66   378.5 1473.03   394.2 1473.75   402.9 1478.23   419.9 1482.51
#Mann= 5 ,-1,0
       0      .1       0  143.87    .045       0   161.5      .1       0
  295.33     .05       0  395.33     .06       0
Bank Sta=143.87,161.5
XS Rating Curve= 0 ,0
Exp/Cntr=0.3,0.1

Type RM Length L Ch R = 1 ,5565    ,286.6,284.4,281.2
XS GIS Cut Line= 4
2182110.08340345686178.9070927872182180.22117552686248.457453429
2182370.34643314686393.2390303662182487.58150489686473.007352726
#Sta/Elev= 30
       0 1506.77     8.9 1502.07    25.7 1494.62    59.3 1481.23    65.3 1477.39
    77.1 1468.42   102.1 1454.94   122.1 1451.17   143.71450.212   150.6  1449.1
   159.2 1450.23     166 1451.43   179.2 1452.25   229.4 1451.42   250.5 1452.81
   304.9 1452.16     331 1453.66   337.7 1455.23   344.8 1459.19   349.6 1460.25
   359.2 1460.65   366.1 1460.08     369 1461.26   379.3 1470.72   382.2 1472.71
   401.6 1483.98   422.2 1493.31   431.9 1496.65   465.6 1511.65   479.6 1517.18
#Mann= 6 ,-1,0
       0      .1       0   143.7    .045       0   159.2      .1       0
  278.78     .05       0  318.78     .06       0  397.75      .1       0
Bank Sta=143.7,159.2
XS Rating Curve= 0 ,0
Exp/Cntr=0.3,0.1

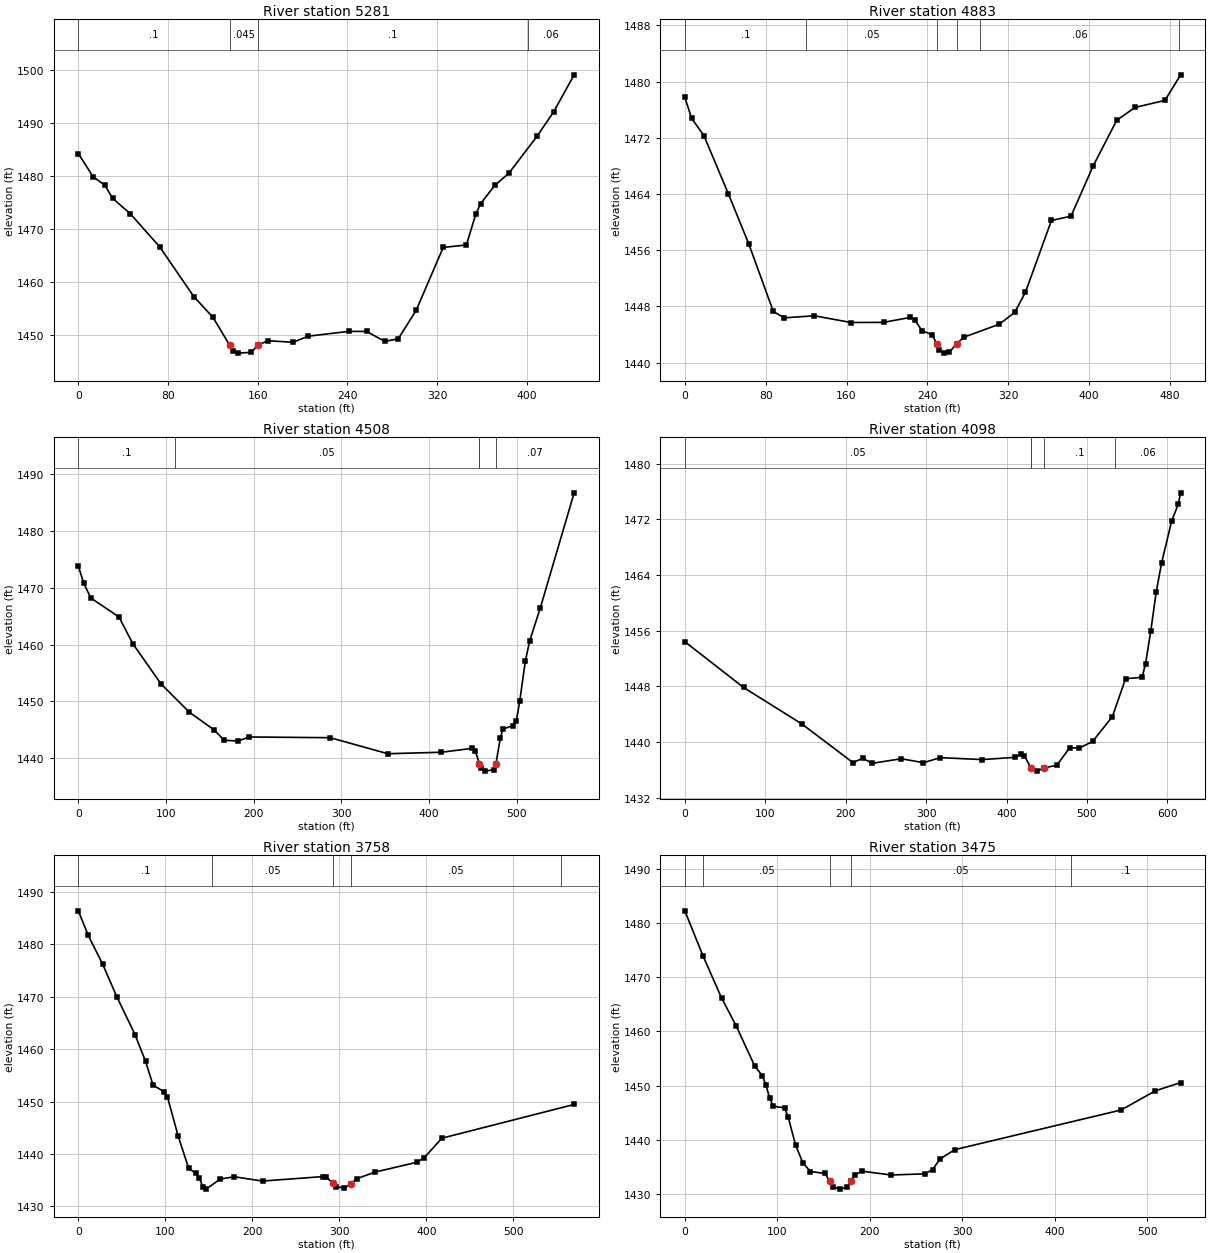
Type RM Length L Ch R = 1 ,5281    ,392.7,397.3,398.5
XS GIS Cut Line= 5
2181980.64621708686414.0757156542182056.52989023686501.822031056
2182172.98424111686559.2664370772182258.05735996686551.320006077
2182363.75221423686584.840259367
#Sta/Elev= 30
       0 1484.28    13.2  1479.9    23.7  1478.3    30.5 1475.84    46.4  1472.9
    72.7 1466.61   103.2 1457.19   120.1 1453.32  135.07 1448.03   137.9 1446.93
   142.4 1446.56   154.1 1446.71   160.2 1448.08   169.1 1448.91   191.4 1448.61
     205 1449.76   241.1 1450.67   257.1 1450.66   273.2 1448.79   285.2 1449.24
   301.3 1454.64   325.4 1466.54   346.1 1467.01   354.5 1472.85   358.7 1474.79
   371.3 1478.25   383.9 1480.55   409.1 1487.55   423.9 1492.17   442.2 1499.17
#Mann= 4 ,-1,0
       0      .1       0  135.07    .045       0   160.2      .1       0
   401.3     .06       0
Bank Sta=135.07,160.2
XS Rating Curve= 0 ,0
Exp/Cntr=0.3,0.1

Type RM Length L Ch R = 1 ,4883    ,371.8,375,374.2
XS GIS Cut Line= 4
2181811.44875503686514.4365821342181843.24543036686733.876993279
2181964.60507948686817.3716218162182072.07624592686874.196853037
#Sta/Elev= 30
       0 1477.75     6.8 1474.76    18.9 1472.31    43.2 1463.99    63.4 1456.85
    87.6 1447.27    98.4 1446.36   128.1 1446.66   164.4  1445.7   196.8 1445.72
   222.9 1446.42   227.6 1446.07   234.6 1444.54   244.9 1443.94  249.31 1442.62
     252 1441.74   256.8 1441.34   261.7 1441.48   268.91442.651   276.3 1443.62
   311.1 1445.45   326.4 1447.13     337 1449.99   362.8 1460.23   382.1 1460.83
   404.1    1468   427.4 1474.49   445.5 1476.32   475.1 1477.32   490.6 1480.96
#Mann= 6 ,-1,0
       0      .1       0     120     .05       0  249.31    .045       0
   268.9     .05       0  291.73     .06       0  489.04      .1       0
Bank Sta=249.31,268.9
XS Rating Curve= 0 ,0
Exp/Cntr=0.3,0.1

Type RM Length L Ch R = 1 ,4508    ,417.9,410.2,403.7
XS GIS Cut Line= 3
2181325.94699691686914.3436753512181552.71995397686928.097991197
2181820.28221479687135.194034619
#Sta/Elev= 30
       0 1473.84     6.2 1470.77    14.3  1468.2    46.3 1464.88    62.3 1460.13
    94.4 1453.08   126.5 1448.13   154.5 1445.04   166.5 1443.17   182.6 1443.06
   194.6 1443.76   287.4 1443.63     353 1440.81   413.7 1441.07   449.1 1441.75
   452.8 1441.28  457.44 1439.03   459.2 1438.33   464.2 1437.75   474.4 1438.02
   476.31439.075   481.3 1443.58   484.2 1445.14   495.6 1445.77   499.6 1446.62
   503.4 1450.02   509.8 1457.12   514.8 1460.67     527 1466.52   565.5 1486.71
#Mann= 5 ,-1,0
       0      .1       0     110     .05       0  457.19     .07       0
  457.44    .045       0   476.3     .07       0
Bank Sta=457.44,476.3
XS Rating Curve= 0 ,0
Exp/Cntr=0.3,0.1

Type RM Length L Ch R = 1 ,4098    ,339.6,340.4,338.9
XS GIS Cut Line= 4
 2181154.0170634687279.4020307472181287.29509091687400.361757946
2181590.82805091687431.8257531222181719.03701731687403.902296835
#Sta/Elev= 30
       0 1454.43    73.1 1447.84   145.5  1442.6     209 1437.05   221.1 1437.66
   233.1 1436.95   269.3  1437.6   296.7 1437.03   317.6 1437.76   369.9 1437.48
   410.1  1437.8   418.1 1438.28   422.2 1438.02   430.2 1436.29   438.2 1435.82
   446.3 1436.29   462.4 1436.65   478.5 1439.18   490.6 1439.15     507 1440.08
   531.6 1443.66   547.9  1449.1   568.4  1449.3   572.8 1451.24   579.3 1455.96
     586 1461.54   592.7 1465.72   605.2 1471.76   613.4 1474.16   616.4 1475.82
#Mann= 5 ,-1,0
       0     .05       0  429.98      .1       0   430.2    .045       0
   446.3      .1       0  535.14     .06       0
Bank Sta=430.2,446.3
XS Rating Curve= 0 ,0
Exp/Cntr=0.3,0.1

Type RM Length L Ch R = 1 ,3758    ,283.4,282.9,279.7
XS GIS Cut Line= 4
2181189.37200672687749.1150653052181289.84341596687721.766431308
2181557.11915946687762.4323740872181752.06680834687752.289744873
#Sta/Elev= 30
       0 1486.34    11.2 1481.73    27.8 1476.22    44.4  1469.9    65.1 1462.76
    77.2 1457.68    85.8 1453.15    98.3 1451.86   102.4 1450.86   114.6 1443.47
   126.7 1437.31   134.8 1436.32   138.9 1435.48   142.9 1433.78   146.9  1433.3
   163.1 1435.23   179.3 1435.65   211.7 1434.84   281.2 1435.69   284.8 1435.61
   292.6 1434.38   296.6 1433.77   305.8 1433.49  313.35 1434.35   319.9 1435.29
   341.2 1436.56   389.1 1438.42   397.6 1439.31   417.6    1443   569.7 1449.44
#Mann= 5 ,-1,0
       0      .1       0  154.13     .05       0   292.6    .045       0
  313.35     .05       0  554.48     .06       0
Bank Sta=292.6,313.35
XS Rating Curve= 0 ,0
Exp/Cntr=0.3,0.1

Type RM Length L Ch R = 1 ,3475    ,279.2,280.7,281.1
XS GIS Cut Line= 3
2181220.53898269687943.2756138342181527.48278577687957.869955811
2181746.34442363687890.994923159
#Sta/Elev= 30
       0  1482.3    19.7 1473.97    39.7 1466.22    55.7 1460.98    75.7 1453.58
    83.7 1451.86    87.7 1450.13    91.7 1447.72    95.7  1446.2   107.8 1445.88
   111.8 1444.18   119.8 1438.99   127.6 1435.75   135.8 1434.11   151.8 1433.75
  156.76 1432.27   159.8 1431.29   167.8 1430.86   175.8 1431.26   179.8  1432.3
   183.8 1433.54   191.9 1434.17   223.2 1433.47   259.9 1433.69   267.9 1434.48
   275.9 1436.43     292 1438.16   471.8 1445.49   508.8 1449.03   536.1 1450.56
#Mann= 5 ,-1,0
       0      .1       0      20     .05       0  156.76    .045       0
   179.8     .05       0  417.29      .1       0
Bank Sta=156.76,179.8
XS Rating Curve= 0 ,0
Exp/Cntr=0.3,0.1

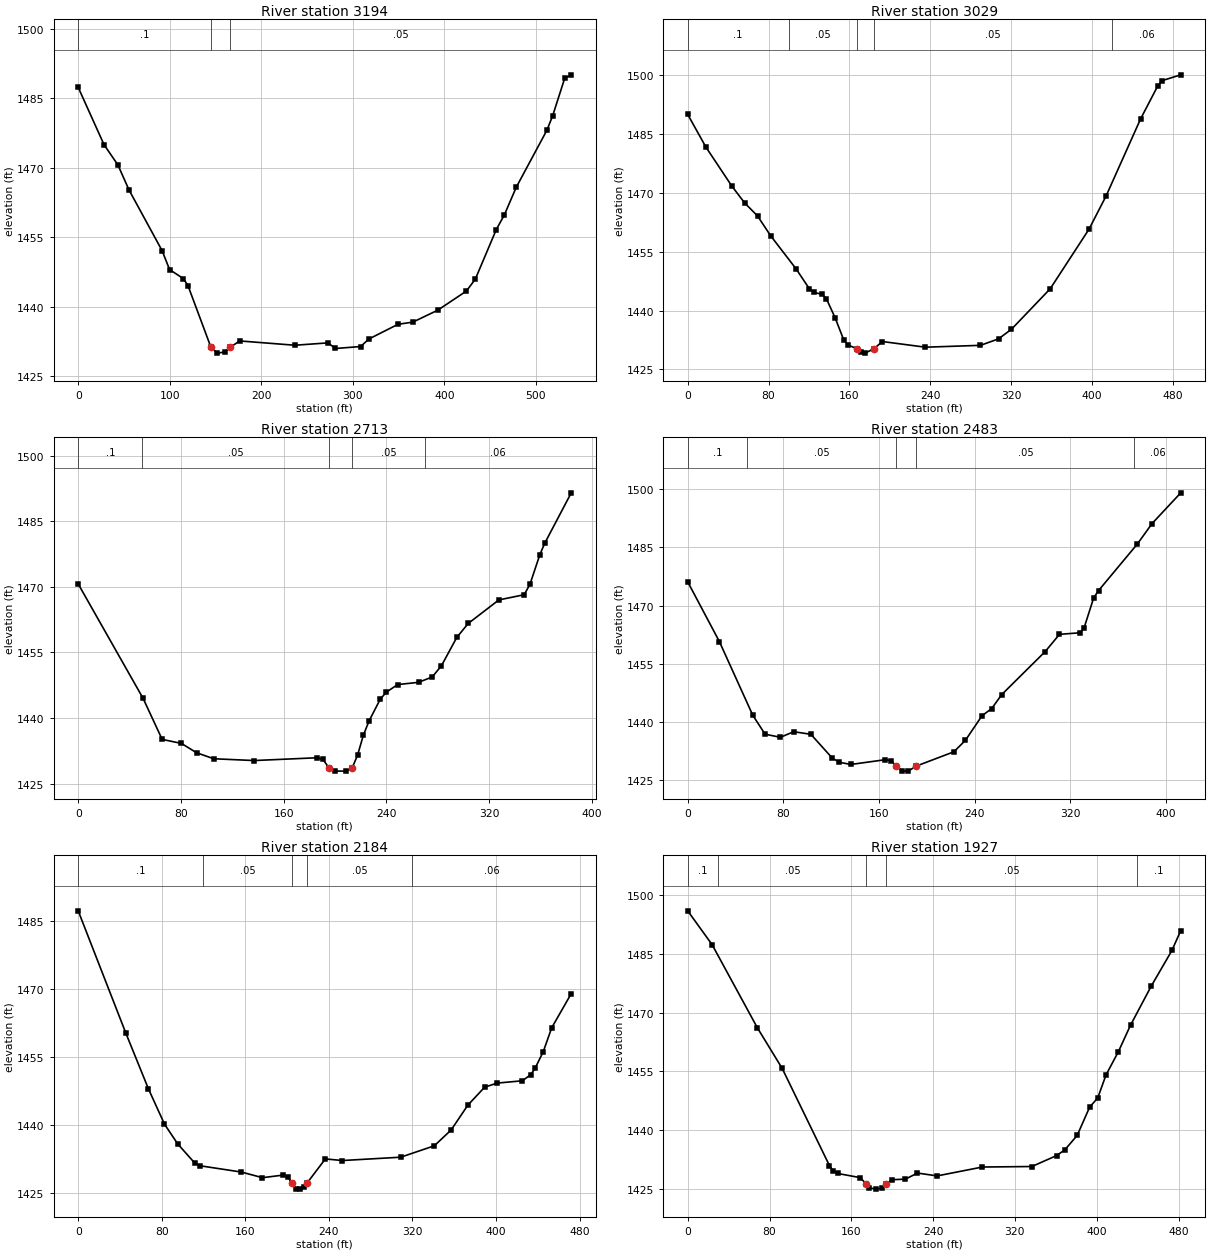
Type RM Length L Ch R = 1 ,3194    ,161.4,165.5,167.9
XS GIS Cut Line= 3
2181181.05355234688197.0345254552181587.56655234688244.126525455
2181698.31527186688310.913386166
#Sta/Elev= 30
       0 1487.32    28.2 1474.97    43.4 1470.59    55.5 1465.21    91.7  1452.1
    99.8 1448.04   114.8 1446.11   119.9 1444.59  145.01 1431.28   152.1 1430.03
   160.2 1430.27   166.21431.295   176.3 1432.66   236.7 1431.73   272.9 1432.24
     281 1431.03   308.5 1431.45   317.6 1433.08   349.4 1436.25   365.5 1436.71
   392.7 1439.28     424  1443.4   433.8 1445.98   456.7 1456.67   465.5 1459.82
   478.5 1465.78     512 1478.08   518.3  1481.2   531.4 1489.26   538.6 1490.02
#Mann= 3 ,-1,0
       0      .1       0  145.01    .045       0   166.2     .05       0
Bank Sta=145.01,166.2
XS Rating Curve= 0 ,0
Exp/Cntr=0.3,0.1

Type RM Length L Ch R = 1 ,3029    ,313.7,315.8,317.7
XS GIS Cut Line= 2
2181147.25124206688317.048791543 2181605.6010336688484.407336209
#Sta/Elev= 30
       0  1489.9      18 1481.59    43.6 1471.69    56.3 1467.39    69.1 1464.07
      82 1459.05   107.4 1450.55   120.2  1445.6   124.5 1444.65     133 1444.11
   137.2 1443.02   145.8  1438.2   154.3 1432.59   158.5 1431.25   167.1 1430.31
   171.3 1429.43   175.5 1429.16  184.41 1430.29   192.6 1432.11   235.2 1430.67
   289.7 1431.14   307.6 1432.79   320.4 1435.24   358.7 1445.53   397.1 1460.69
     414 1469.14   448.1 1488.73   465.1 1497.13   469.4 1498.49   487.9 1499.97
#Mann= 5 ,-1,0
       0      .1       0     100     .05       0   167.1    .045       0
  184.41     .05       0     420     .06       0
Bank Sta=167.1,184.41
XS Rating Curve= 0 ,0
Exp/Cntr=0.3,0.1

Type RM Length L Ch R = 1 ,2713    ,225.1,229.9,229.3
XS GIS Cut Line= 2
2181101.79116617688587.6140134422181444.92780499688760.174875106
#Sta/Elev= 30
       0 1470.68    50.6 1444.48    65.4 1435.12    80.4  1434.2    92.2 1432.07
   105.6 1430.69     137 1430.28   186.2 1430.92   190.7 1430.53   195.2 1428.66
   199.7 1427.88   208.3 1427.86   213.4  1428.6   217.6 1431.48   222.1 1436.03
   226.5 1439.29   235.3 1444.31     240 1445.92   248.9 1447.66   265.1 1448.17
   275.8  1449.4     283 1451.98   294.9 1458.43   303.8 1461.63   327.7 1467.02
   347.4 1468.21   351.9 1470.57   359.6 1477.35   363.4 1479.97   384.1 1491.52
#Mann= 5 ,-1,0
       0      .1       0      50     .05       0   195.2    .045       0
   213.4     .05       0     270     .06       0
Bank Sta=195.2,213.4
XS Rating Curve= 0 ,0
Exp/Cntr=0.3,0.1

Type RM Length L Ch R = 1 ,2483    ,284.6,298.8,308.1
XS GIS Cut Line= 3
2181006.05186839688755.9534505182181209.59553218688889.545645533
2181375.86092411688919.024010584
#Sta/Elev= 30
       0 1476.11    26.5 1460.72    54.4 1441.76    64.7 1436.87    77.5 1436.07
    88.7 1437.51     103 1436.84   120.9 1430.72   126.9 1429.63   136.5 1429.08
   165.2  1430.3     170 1430.06   174.5 1428.64   179.6 1427.36   184.4 1427.37
   191.21428.666   222.6 1432.34   232.2 1435.28   246.1 1441.62   254.2 1443.47
   262.6 1447.07   298.9 1458.14   310.9 1462.58   328.2 1462.99   331.4 1464.19
   339.5 1471.99   343.6 1473.87   376.1 1485.88   388.3 1491.11   412.3 1499.02
#Mann= 5 ,-1,0
       0      .1       0      50     .05       0   174.5    .045       0
   191.2     .05       0  373.47     .06       0
Bank Sta=174.5,191.2
XS Rating Curve= 0 ,0
Exp/Cntr=0.3,0.1

Type RM Length L Ch R = 1 ,2184    ,260.8,257.3,250.8
XS GIS Cut Line= 3
2180900.01864588688831.3540397762180936.77138659688934.623384641
2180966.23446696 689295.81892547
#Sta/Elev= 30
       0 1487.27    45.4 1460.36    67.3 1447.88    82.6 1440.12    95.3 1435.73
   111.4 1431.56   116.2 1430.93   156.3 1429.52   176.4 1428.28   196.5 1428.86
   200.5 1428.53  204.66 1427.15   208.5 1425.87   212.5 1425.75   216.5 1426.11
   219.41427.192   236.6 1432.43   252.9 1432.07   308.8 1432.81   340.9 1435.33
     357 1438.82     373 1444.31   389.1 1448.29   401.1 1449.19   425.2  1449.7
   433.2 1451.05   437.3 1452.44   445.2 1456.14   453.3 1461.43     472 1468.97
#Mann= 5 ,-1,0
       0      .1       0  119.61     .05       0  204.66    .045       0
   219.4     .05       0  319.61     .06       0
Bank Sta=204.66,219.4
XS Rating Curve= 0 ,0
Exp/Cntr=0.3,0.1

Type RM Length L Ch R = 1 ,1927    ,370,375.6,374.6
XS GIS Cut Line= 4
2180695.02596525 688913.372326512180681.42469006689037.198553335
2180751.82404855689186.3508522462180773.97411301689377.729938465
#Sta/Elev= 30
       0 1496.04    23.9 1487.38    68.2 1466.11    92.4 1455.76   138.6 1430.93
   142.2 1429.56   146.7  1428.9   168.7 1427.84   174.7 1426.19   177.7 1425.26
   183.7  1424.9   189.7 1425.17  194.34 1426.19   199.7  1427.3     213 1427.46
   224.7 1429.01     244 1428.28   288.2 1430.55   336.6 1430.68   360.8 1433.48
   368.9 1434.96   380.9 1438.63     393 1445.81   401.1 1448.27   409.1 1454.09
   421.2 1460.04   433.1 1466.83   453.4 1476.83   473.6 1485.93   482.2 1491.01
#Mann= 5 ,-1,0
       0      .1       0      30     .05       0   174.7    .045       0
  194.34     .05       0   439.5      .1       0
Bank Sta=174.7,194.34
XS Rating Curve= 0 ,0
Exp/Cntr=0.3,0.1