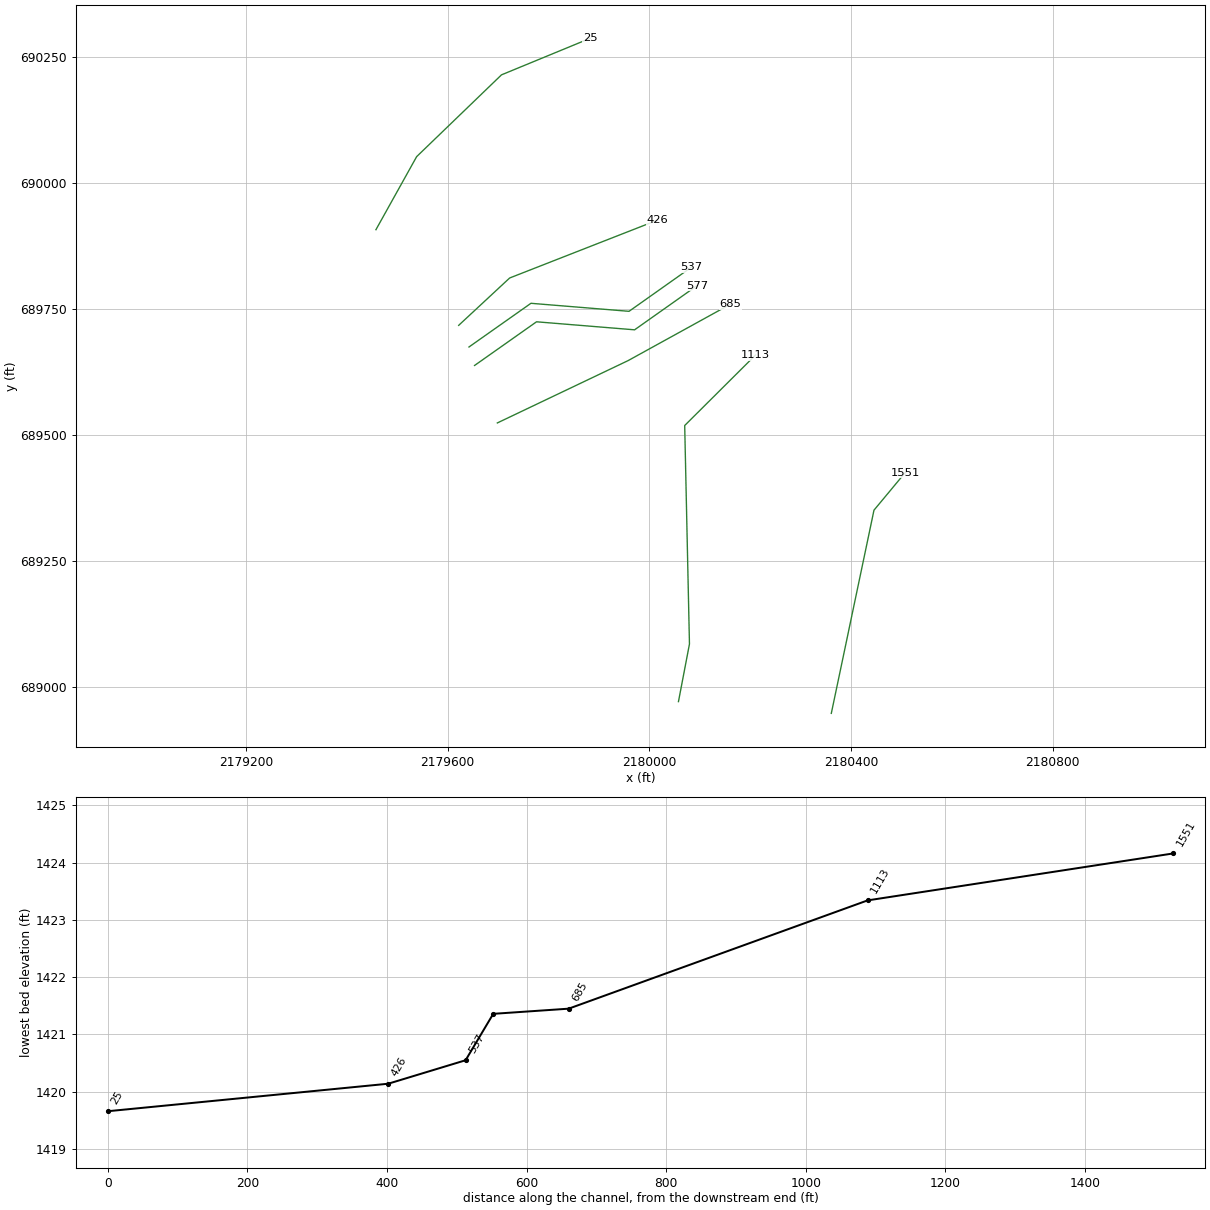
HEC-RAS study GRANDCMPRN.prj: GRANDCMPRN

--- GRANDCMPRN.g01 (geometry) --- (continued)

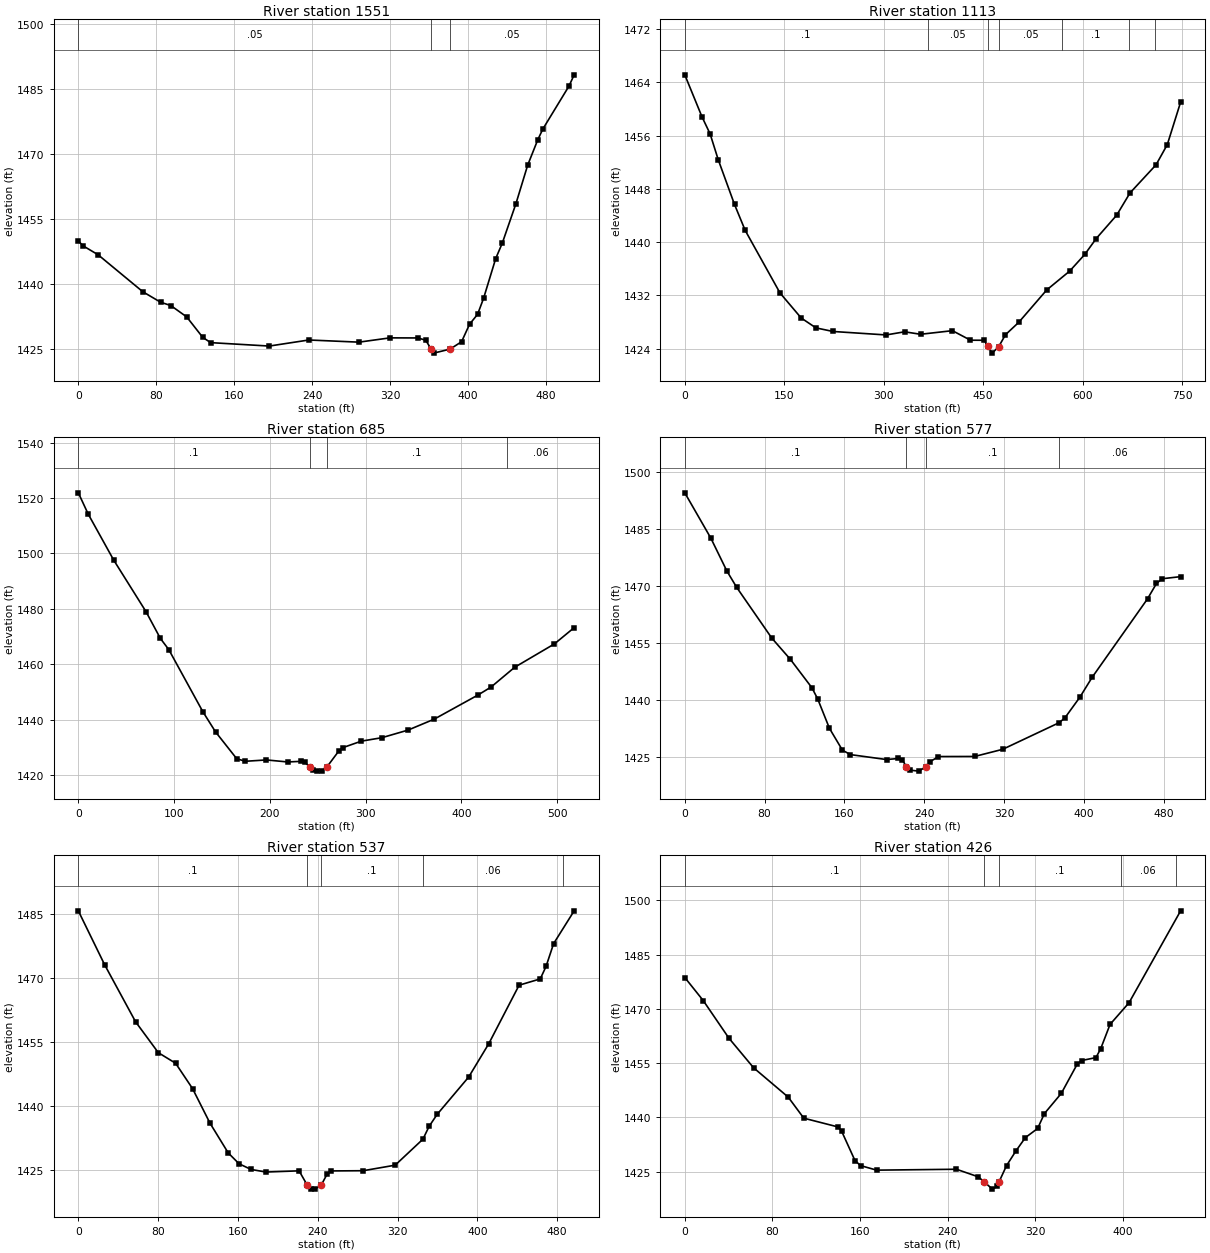
Type RM Length L Ch R = 1 ,1551    ,433.9,438.1,437.9
XS GIS Cut Line= 3
2180361.00647326688948.3443125182180445.62266965689351.270415197
2180507.63363838689425.818941846
#Sta/Elev= 30
       0 1450.03     4.9  1448.9    20.3 1446.84    66.2 1438.31    84.4  1435.9
    94.9 1435.13   111.2 1432.51   127.6 1427.81   135.7 1426.58   195.9 1425.79
   236.5 1427.19   287.9 1426.69   319.7 1427.68   348.3 1427.66   356.4 1427.14
     3621425.078   364.6 1424.16  381.44 1425.09   393.2 1426.79   401.4 1430.83
   409.6  1433.1   415.7 1436.76   428.2 1445.96     435 1449.55     449 1458.65
     461  1467.5   471.4 1473.38   476.6 1475.85   503.3 1485.71   508.7 1488.34
#Mann= 3 ,-1,0
       0     .05       0     362    .045       0  381.44     .05       0
Bank Sta=362,381.44
XS Rating Curve= 0 ,0
Exp/Cntr=0.3,0.1

Type RM Length L Ch R = 1 ,1113    ,438,428.3,405.9
XS GIS Cut Line= 4
2180057.94025894688971.6552276672180079.75170441689085.854332751
2180070.30566965689519.0943705782180210.85860263689658.988057967
#Sta/Elev= 30
       0 1465.11      26 1458.79    38.2 1456.24    50.4 1452.38      75 1445.65
    91.1 1441.76   143.6 1432.37   175.6 1428.61   197.8 1427.13   223.6 1426.59
   303.6 1426.07   331.6 1426.54   355.6 1426.17   403.7 1426.71   430.9 1425.28
   451.7 1425.27   456.81424.376   463.7 1423.34  473.55 1424.32   483.7  1426.1
   503.7 1427.96   545.9 1432.82   580.5 1435.65   603.3 1438.15   620.6 1440.54
   651.4 1444.04   671.6 1447.39   710.8  1451.6   727.8 1454.64   747.9 1461.02
#Mann= 7 ,-1,0
       0      .1       0  366.26     .05       0   456.8    .045       0
  473.55     .05       0  569.61      .1       0  669.61     .05       0
  709.61     .06       0
Bank Sta=456.8,473.55
XS Rating Curve= 0 ,0
Exp/Cntr=0.3,0.1

Type RM Length L Ch R = 1 ,685     ,117.1,108,101.6
XS GIS Cut Line= 3
2179698.83670626689524.2194581922179958.11747412689647.814900085
2180160.15225083689759.128149967
#Sta/Elev= 30
       0 1521.89    10.3 1514.22    36.9 1497.64    70.7    1479    85.7 1469.34
    94.5  1465.3     130 1442.93   143.3 1435.62   165.4 1425.94   174.3    1425
   196.5 1425.49   218.6 1424.76   232.8 1424.98   236.3 1424.75  241.59    1423
   245.2 1421.88   249.6 1421.45   254.1 1421.62   259.8 1423.03   271.8 1428.59
   276.2 1429.92   295.6 1432.27     317 1433.51   344.4 1436.26   371.8 1440.22
   417.5 1448.93   431.2 1451.82   455.8 1458.94   497.3 1467.37   517.9 1473.23
#Mann= 4 ,-1,0
       0      .1       0  241.59    .045       0   259.8      .1       0
  447.23     .06       0
Bank Sta=241.59,259.8
XS Rating Curve= 0 ,0
Exp/Cntr=0.3,0.1

Type RM Length L Ch R = 1 ,577     ,36.6,39.6,39.1
XS GIS Cut Line= 4
2179653.64878037689638.1417264842179776.50982551 689724.76318277
2179970.96615595689708.853119371 2180094.7110935689796.358468069
#Sta/Elev= 30
       0 1494.64    26.1 1482.71    42.2 1474.04      52 1469.75    87.2 1456.39
   105.9 1450.77   127.4 1443.32   133.2 1440.38     145 1432.62     158 1426.88
     166 1425.71   202.2 1424.41   214.2 1424.69   218.2 1424.23   222.2 1422.52
   226.2 1421.61   234.3 1421.36   242.2 1422.53   246.1 1423.87   254.3  1425.2
   290.5 1425.22   318.6  1427.1   375.2 1434.11     381 1435.38   395.9 1440.78
   408.3 1446.06   463.8 1466.72   472.8 1470.77   478.5 1472.02     497 1472.57
#Mann= 4 ,-1,0
       0      .1       0   222.2    .045       0   242.2      .1       0
  375.43     .06       0
Bank Sta=222.2,242.2
XS Rating Curve= 0 ,0
Exp/Cntr(USF)=0,0
Exp/Cntr=0.3,0.1

Type RM Length L Ch R = 1 ,537     ,105.5,110.9,116
XS GIS Cut Line= 4
2179642.60012523689674.8232615442179765.46117037689761.444717831
2179959.91750081689745.5346544312180083.66243836689833.040003129
#Sta/Elev= 30
       0 1485.69    26.4 1473.06    57.4 1459.72    80.2 1452.49    97.5 1450.02
   114.5 1444.08     132 1435.98   150.3 1429.01   161.1 1426.49   173.1 1425.16
     188 1424.55   221.3 1424.83   229.3 1421.54   233.3 1420.56   237.3 1420.55
  243.54 1421.53   249.4 1424.08   253.4 1424.81   285.5 1424.86   317.6 1426.16
   345.4 1432.24   351.7 1435.28   359.7 1438.06   391.3  1446.8   411.4 1454.59
   441.8 1468.29     463 1469.76   468.8 1472.67   476.4 1478.02     497  1485.7
#Mann= 5 ,-1,0
       0      .1       0   229.3    .045       0  243.54      .1       0
  345.43     .06       0  485.43      .1       0
Bank Sta=229.3,243.54
XS Rating Curve= 0 ,0
Exp/Cntr(USF)=0,0
Exp/Cntr=0.3,0.1

Type RM Length L Ch R = 1 ,426     ,395.6,401.7,401.3
XS GIS Cut Line= 3
2179622.17820097689717.7317768132179723.24843193689811.628212525
2180016.17815635689926.279745543
#Sta/Elev= 30
       0 1478.69    16.8 1472.32    40.3 1461.89    62.8 1453.71    94.4 1445.59
   108.6 1439.77   139.9 1437.34   143.2 1436.12   155.3 1428.05   160.4 1426.65
   175.1 1425.39   247.9 1425.64   267.8 1423.55   273.4 1422.11   280.7 1420.14
     285 1420.88  286.65 1422.06   293.6 1426.63   302.2 1430.71   310.8 1434.39
     322 1436.92   328.2 1441.05   343.6 1446.63     358 1454.65   362.1 1455.72
   375.2 1456.53   379.5 1458.94   388.1 1465.72   405.4  1471.7   452.5 1497.14
#Mann= 5 ,-1,0
       0      .1       0   273.4    .045       0  286.65      .1       0
  397.96     .06       0  447.96      .1       0
Bank Sta=273.4,286.65
XS Rating Curve= 0 ,0
Exp/Cntr=0.3,0.1

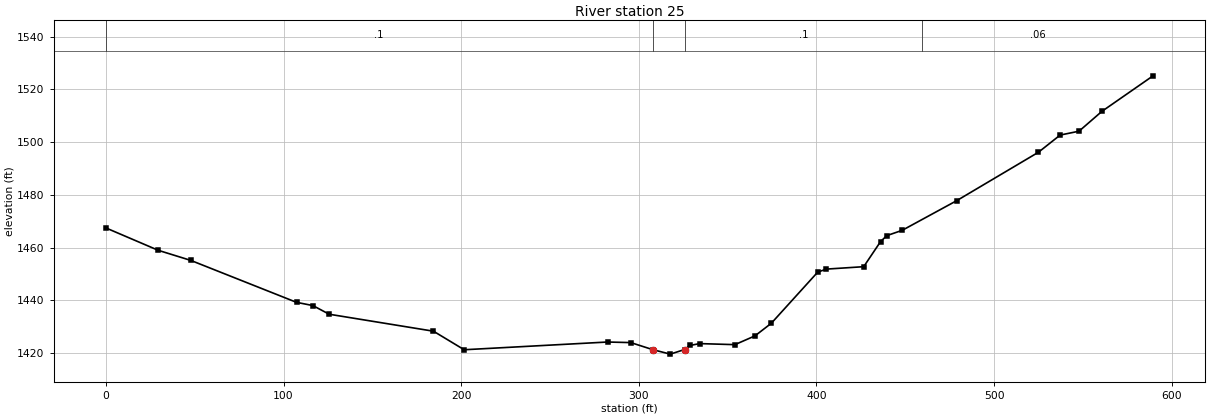
Type RM Length L Ch R = 1 ,25      ,,,
XS GIS Cut Line= 4
2179458.12212338689907.4220612852179538.82619671690052.236847083
2179707.02253647 690214.399237432179882.76131298690286.806630329
#Sta/Elev= 30
       0 1467.49    29.5    1459    47.8 1455.18   107.3 1439.29   116.5 1438.07
   125.7 1434.78   184.4 1428.35   201.7 1421.32   282.4 1424.25   295.5 1424.03
  307.76 1421.38   317.7 1419.66   325.8 1421.41   328.8 1422.95   334.3 1423.65
   354.1 1423.25   365.4 1426.58   374.6 1431.36   400.7 1450.73   405.5 1451.88
   426.6  1452.8   436.1 1462.32   439.6 1464.57   448.3 1466.59     479 1477.84
     525 1496.19   537.2 1502.69   547.8 1504.15   560.7 1511.67589.4932 1525.14
#Mann= 4 ,-1,0
       0      .1       0  307.76    .045       0   325.8      .1       0
  459.42     .06       0
Bank Sta=307.76,325.8
XS Rating Curve= 0 ,0
Exp/Cntr(USF)=0,0
Exp/Cntr=0.3,0.1
LCMann Table=0

Chan Stop Cuts=-1
Use User Specified Reach Order=0
Composite Channel Slope=5